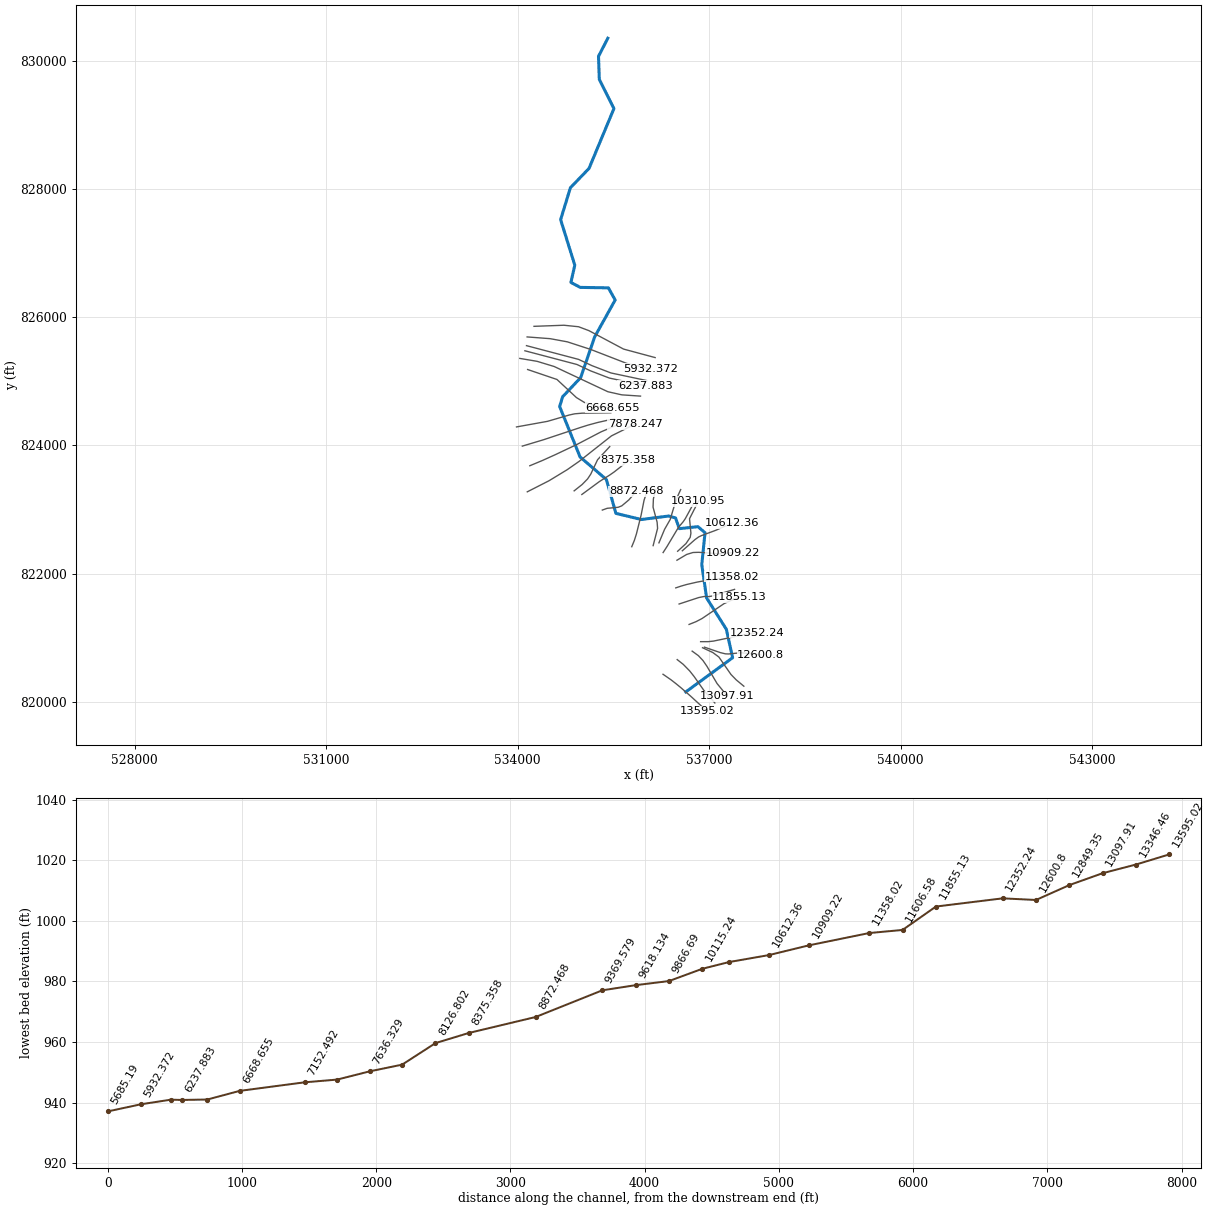
--- 7989_ras.prj (project) ---

Proj Title=7989
Current Plan=p01
Default Exp/Contr=0.3,0.1
English Units
Geom File=g01
Flow File=f01
Plan File=p01
Y Axis Title=Elevation
X Axis Title(PF)=Main Channel Distance
X Axis Title(XS)=Station
BEGIN DESCRIPTION:
RFD model 7989 exported to HEC-RAS
END DESCRIPTION:

--- 7989_ras.p01 (plan) ---

Plan Title=Plan 01
Program Version=4.10
Short Identifier=Plan 01
Geom File=g01
Flow File=f01
Subcritical Flow
Calc Critical at every XS
Secant Critical Depth

--- 7989_ras.f01 (steady flow) ---

Flow Title=Flow 01
Program Version=5.01
Number of Profiles= 6
Profile Names=10yr,25yr,50yr,100yr,100plus,500yr
River Rch & RM=7989,47,13595.02
 8976.8111706.1413880.4916180.79 19809.922016.58
River Rch & RM=7989,47,13346.46
 8979.3811709.4613884.3916185.3219815.45 22022.7
River Rch & RM=7989,47,13097.91
 8984.1811715.6413891.6816193.78 19825.822034.12
River Rch & RM=7989,47,12849.35
 8987.09 11719.4 13896.116198.9119832.0822041.05
River Rch & RM=7989,47, 12600.8
 9176.9411964.1314184.4116533.3520241.5322492.65
River Rch & RM=7989,47,12352.24
 9178.8111966.5514187.2616536.6520245.57 22497.1
River Rch & RM=7989,47,11855.13
 9231.4312034.3714267.1516629.3220359.0322622.22
River Rch & RM=7989,47,11606.58
 9234.8412038.7514272.3216635.3120366.3622630.32
River Rch & RM=7989,47,11358.02
 9281.43 12098.814343.0516717.3620466.8122741.08
River Rch & RM=7989,47,10909.22
 9350.8712188.2914448.4516839.6120616.4822906.13
River Rch & RM=7989,47,10612.36
 9364.7712206.2114469.5616864.0920646.4522939.18
River Rch & RM=7989,47,10310.95
 9375.1112219.5314485.2516882.2920668.7422963.75
River Rch & RM=7989,47,10115.24
 9377.9912223.2414489.6316887.3720674.95 22970.6
River Rch & RM=7989,47, 9866.69
 9379.8612225.6414492.4616890.6520678.9622975.03
River Rch & RM=7989,47,9618.134
 9388.1612236.3514505.0616905.2620696.8622994.76
River Rch & RM=7989,47,9369.579
  9392.4 12241.814511.4916912.7220705.9923004.83
River Rch & RM=7989,47,8872.468
 9399.5112250.9714522.2916925.2420721.3223021.73
River Rch & RM=7989,47,8375.358
 9418.1412274.9814550.5616958.0320761.46   23066
River Rch & RM=7989,47,8126.802
 9420.1712277.5914553.6416961.6120765.8423070.82
River Rch & RM=7989,47,7878.247
 9422.3712280.4314556.9816965.4820770.5923076.05
River Rch & RM=7989,47,7636.329
10606.3413804.9816351.9219046.6523318.5325884.26
River Rch & RM=7989,47, 7394.41
10609.7913809.4216357.1419052.7123325.9425892.42
River Rch & RM=7989,47,7152.492
10615.3813816.6116365.5919062.5123337.9425905.64
River Rch & RM=7989,47,6668.655
10681.9913902.3216466.4719179.44 23481.126063.35
River Rch & RM=7989,47,6426.736
 10693.313916.88 16483.619199.29 23505.426090.13
River Rch & RM=7989,47,6237.883
 10699.213924.4716492.5319209.6523518.0826104.09
River Rch & RM=7989,47,6153.681
10700.0213925.5216493.7819211.0923519.8426106.03
River Rch & RM=7989,47,5932.372
10701.4913927.4216496.0119213.6723523.0126109.52
River Rch & RM=7989,47, 5685.19
10706.5713933.95 16503.719222.5923533.9226121.55
River Rch & RM=7989,47,5438.008
   1073013964.0916539.17 19263.723584.2626176.99
River Rch & RM=7989,47,4905.325
10769.1214014.42 16598.419332.3523668.3126269.58
River Rch & RM=7989,47,4202.097
10802.6414057.5616649.1619391.1823740.3326348.92
River Rch & RM=7989,47,3707.732
10816.8614075.8516670.6919416.1423770.8826382.57
River Rch & RM=7989,47, 3381.56
10824.7114085.9416682.56 19429.923787.7326401.13
River Rch & RM=7989,47,2966.186
10858.3514129.2316733.4919488.9323860.0126480.74
River Rch & RM=7989,47,2719.004
10864.8814137.6316743.3819500.3923874.0326496.19
River Rch & RM=7989,47,2471.822
10897.8414180.0316793.2719558.2223944.8326574.17
River Rch & RM=7989,47, 2224.64
10902.0814185.4816799.6919565.6623953.94 26584.2
River Rch & RM=7989,47,1977.457
10911.8714198.07 16814.519582.8223974.9626607.35
River Rch & RM=7989,47,1730.275
10919.3614207.7216825.8619595.9823991.0626625.09
River Rch & RM=7989,47,1483.093
10923.7714213.3816832.52 19603.724000.52 26635.5
River Rch & RM=7989,47,1235.911
10927.1914217.78 16837.719609.7124007.87 26643.6
River Rch & RM=7989,47,988.7287
10927.8414218.6216838.6919610.8524009.2726645.14
River Rch & RM=7989,47,741.5465
10954.56   1425316879.1319657.7324066.6626708.36
River Rch & RM=7989,47,494.3643
10958.15 14257.616884.5619664.0224074.3626716.83
River Rch & RM=7989,47,247.1822
10963.3614264.3116892.4519673.1624085.5526729.16
River Rch & RM=7989,47,       0
10973.7814277.7116908.2219691.4424107.9326753.81
Boundary for River Rch & Prof#=7989,47,1
Up Type= 0
Dn Type= 2
Boundary for River Rch & Prof#=7989,47,2
Up Type= 0
Dn Type= 2
Boundary for River Rch & Prof#=7989,47,2
Up Type= 0
Dn Type= 2
Boundary for River Rch & Prof#=7989,47,2
Up Type= 0
Dn Type= 2
Boundary for River Rch & Prof#=7989,47,2
Up Type= 0
Dn Type= 2
Boundary for River Rch & Prof#=7989,47,2
Up Type= 0
Dn Type= 2

--- 7989_ras.g01 (geometry) ---

Geom Title=7989
Program Version=4.10

River Reach=7989,47
Reach XY= 30
536632.559653727820151.869614098537366.488343872820685.720853886
537268.026873497821130.159864603  536959.2248319821618.273161269
536883.361612803822140.568910295536934.372694007822638.165369661
536822.275827534822732.171760403536530.876911846822701.136383678
536472.870663918822868.445804648536363.695722269822898.457857565
535937.694327722822843.962809859535538.389940243822939.766665465
535389.060988359823468.211192476534977.422781272823820.289311537
534657.183090192824608.222669303534703.653989032 824759.75205874
534986.538277583825059.498367514535206.476444773825696.972806989
535526.920702368826270.378447704 535420.73341948 826460.69732084
 534980.14663762826467.933062405534833.497744349826545.766596883
534894.557578769 826814.38896566 534672.66747815827525.270155304
534825.479020052828023.542731714535117.391510298828325.408067012
 535507.75934509829259.864879063535278.459125016829714.713131189
535265.978273884830075.718628053535411.766237366830357.990547791

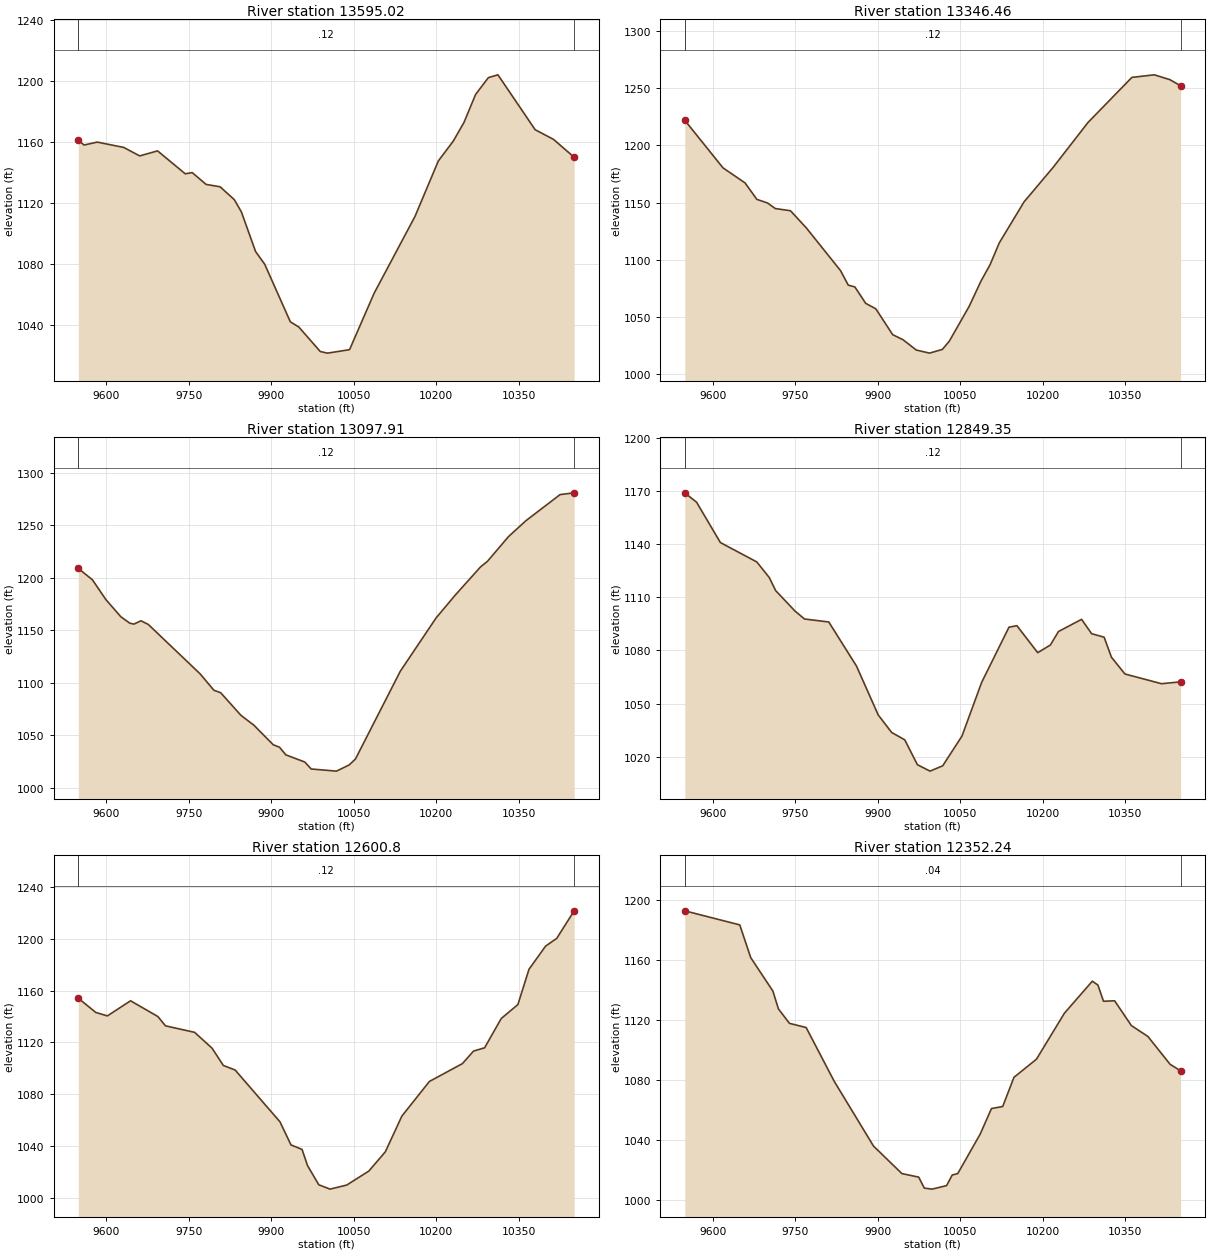
Type RM Length L Ch R = 1 ,13595.02,248.555300,248.555300,248.555300
XS GIS Cut Line= 6
536276.366406656820427.738013964 536399.82589322820342.443987334
536475.106269547820284.394554473536559.763541313820215.294189796
536712.757136274820082.381020496536967.360141524819849.746055995
#Sta/Elev= 30
9549.0191161.303  9559.41158.058 9583.451159.977 9631.55 1156.519660.624 1150.94
9693.1451154.2459743.5191139.2419756.1471140.0259781.4031132.3149806.9361130.742
9832.7521122.3419845.6611114.2899871.4771088.3789888.0931080.0699934.7141042.399
9950.1231038.9929989.1881022.95210002.371021.917 10042.41024.17210087.051061.043
10161.531111.41410203.97 1147.6910231.061160.60810250.481172.776 10271.71191.156
10294.961202.16510312.341203.99310380.071168.07810413.561161.73510450.991150.056
#Mann= 3 , 0 , 0
9549.019    0.12       09549.019    0.12       010450.99    0.12       0
#XS Ineff= 2 , 0
       0                               0
Bank Sta=9549.019,10450.99
Exp/Cntr=0.3,0.1

Type RM Length L Ch R = 1 ,13346.46,248.555300,248.555300,248.555300
XS GIS Cut Line= 6
536498.554511842820656.626526285536593.063667947 820582.65110299
 536693.58159396 820480.12384202536764.765558243820390.580093992
536913.851207919820179.321707264537088.191041705819979.798618988
#Sta/Elev= 30
9549.071 1221.749618.4821180.2799658.6791167.1019680.1721152.7599699.6431149.566
9713.5421144.7579741.3391142.8149770.3661127.7039832.4451090.5159846.391 1077.88
9858.4131076.3469878.0651062.046 9896.541057.2389927.2241034.6769946.0061030.263
9970.1151021.2659994.2241018.56410017.541021.79910030.14 1028.9610066.311059.364
10087.781081.39310104.451095.84110121.121114.799 10166.31150.64610219.051180.649
 10282.4  1219.8 10362.31259.19210403.091261.42310431.471257.20310450.951251.848
#Mann= 3 , 0 , 0
9549.071    0.12       09549.071    0.12       010450.95    0.12       0
#XS Ineff= 2 , 0
       0                               0
Bank Sta=9549.071,10450.95
Exp/Cntr=0.3,0.1

Type RM Length L Ch R = 1 ,13097.91,248.555300,248.555300,248.555300
XS GIS Cut Line= 6
536732.694742165820788.760918546536829.904467672 820718.55460656
536901.700423972 820642.68767358536964.004154083820552.489293237
537122.899986633820282.853740527537284.218862206820086.377183435
#Sta/Elev= 30
9549.0951208.9419574.6941198.1559599.2661179.2249626.4581162.8499642.603 1156.79
9650.1691155.8769662.9071159.0259676.2811155.5929770.6511108.4379795.6831092.811
 9808.111090.4339844.7181068.9789868.5031059.4459903.526 1040.889915.0441038.495
9926.5621031.2149961.1161024.3719972.6341017.74110018.661015.70510041.661021.577
10053.161027.24610134.751110.95810200.051161.91610234.561183.44610280.571210.354
 10293.3 1215.7510331.491239.26610363.311254.48310425.361279.34610450.96 1281.03
#Mann= 3 , 0 , 0
9549.095    0.12       09549.095    0.12       010450.96    0.12       0
#XS Ineff= 2 , 0
       0                               0
Bank Sta=9549.095,10450.96
Exp/Cntr=0.3,0.1

Type RM Length L Ch R = 1 ,12849.35,248.555300,248.555300,248.555300
XS GIS Cut Line= 6
536895.147900028820842.110962535537055.726178701820767.335329349
537151.041256817 820696.96111963537340.714041592820424.578572498
537422.592151743 820340.51545677537542.301272168820241.326900101
#Sta/Elev= 30
9549.1241169.1369570.6011163.8059613.8751141.0169680.1281130.0519702.8771121.205
9714.2521113.9139749.5761102.2719766.8821097.7959810.9871096.1139861.4811071.148
9900.9881043.5219925.404 1033.639949.1971029.4859972.212 1015.419995.201 1011.78
 10018.21014.79210053.231031.574 10089.11061.98410138.791093.15810153.18 1094.02
10191.021078.75310214.021083.07610228.841090.72910270.831097.61210289.021089.498
10311.861087.509 10325.11076.19310349.631066.70710416.291061.20410450.951062.268
#Mann= 3 , 0 , 0
9549.124    0.12       09549.124    0.12       010450.95    0.12       0
#XS Ineff= 2 , 0
       0                               0
Bank Sta=9549.124,10450.95
Exp/Cntr=0.3,0.1

Type RM Length L Ch R = 1 , 12600.8,248.555300,248.555300,248.555300
XS GIS Cut Line= 6
536924.841284855820851.195967931 537174.36198625820765.705761135
537253.111085525820746.691336245537304.157513726820744.629889979
537498.211161631820764.292236742537806.437662733820730.658202098
#Sta/Elev= 30
9549.0711154.0529580.8191143.1369601.8731140.422 9644.031152.1029693.7211139.976
9707.5871132.7799760.552 1127.789792.3311115.5449812.8411102.2299834.2731098.738
9915.9021058.742 9935.921040.9359955.9931037.4999966.061 1024.939986.4241010.248
10006.891006.86410037.341010.009 10077.51020.80410107.531035.65910137.531063.151
 10187.61089.88210247.831103.68510267.92 1113.3310288.071115.85210318.341138.445
10348.611149.17610368.791176.39410399.051194.27810419.231200.21710450.951221.472
#Mann= 3 , 0 , 0
9549.071    0.12       09549.071    0.12       010450.95    0.12       0
#XS Ineff= 2 , 0
       0                               0
Bank Sta=9549.071,10450.95
Exp/Cntr=0.3,0.1

Type RM Length L Ch R = 1 ,12352.24,497.110600,497.110600,497.110600
XS GIS Cut Line= 6
536865.049674332820936.811603551536985.096885803820937.001704612
537066.653293093820945.654205092 537537.90316291821043.341180808
537655.765663845821062.749933687537754.022209598821074.774091333
#Sta/Elev= 30
 9549.061193.0689649.0471183.6839669.0531161.8059709.2771139.5549719.3331127.684
9739.4451118.0129769.8221115.195 9820.75  1079.49892.3161036.1419943.9941017.763
9974.536 1015.419984.6951008.087    9999  1007.410025.31 1009.7510035.471016.787
10045.621017.79210086.481044.18210106.921061.17310127.361062.512 10147.8 1081.99
10188.681094.06110239.731124.835 10290.41146.14110300.531143.53810310.67 1132.74
10330.941133.04410361.291116.55510391.511109.23210431.81 1090.6810450.971086.327
#Mann= 3 , 0 , 0
 9549.06    0.04       0 9549.06    0.04       010450.97    0.04       0
#XS Ineff= 2 , 0
       0                               0
Bank Sta=9549.06,10450.97
Exp/Cntr=0.3,0.1

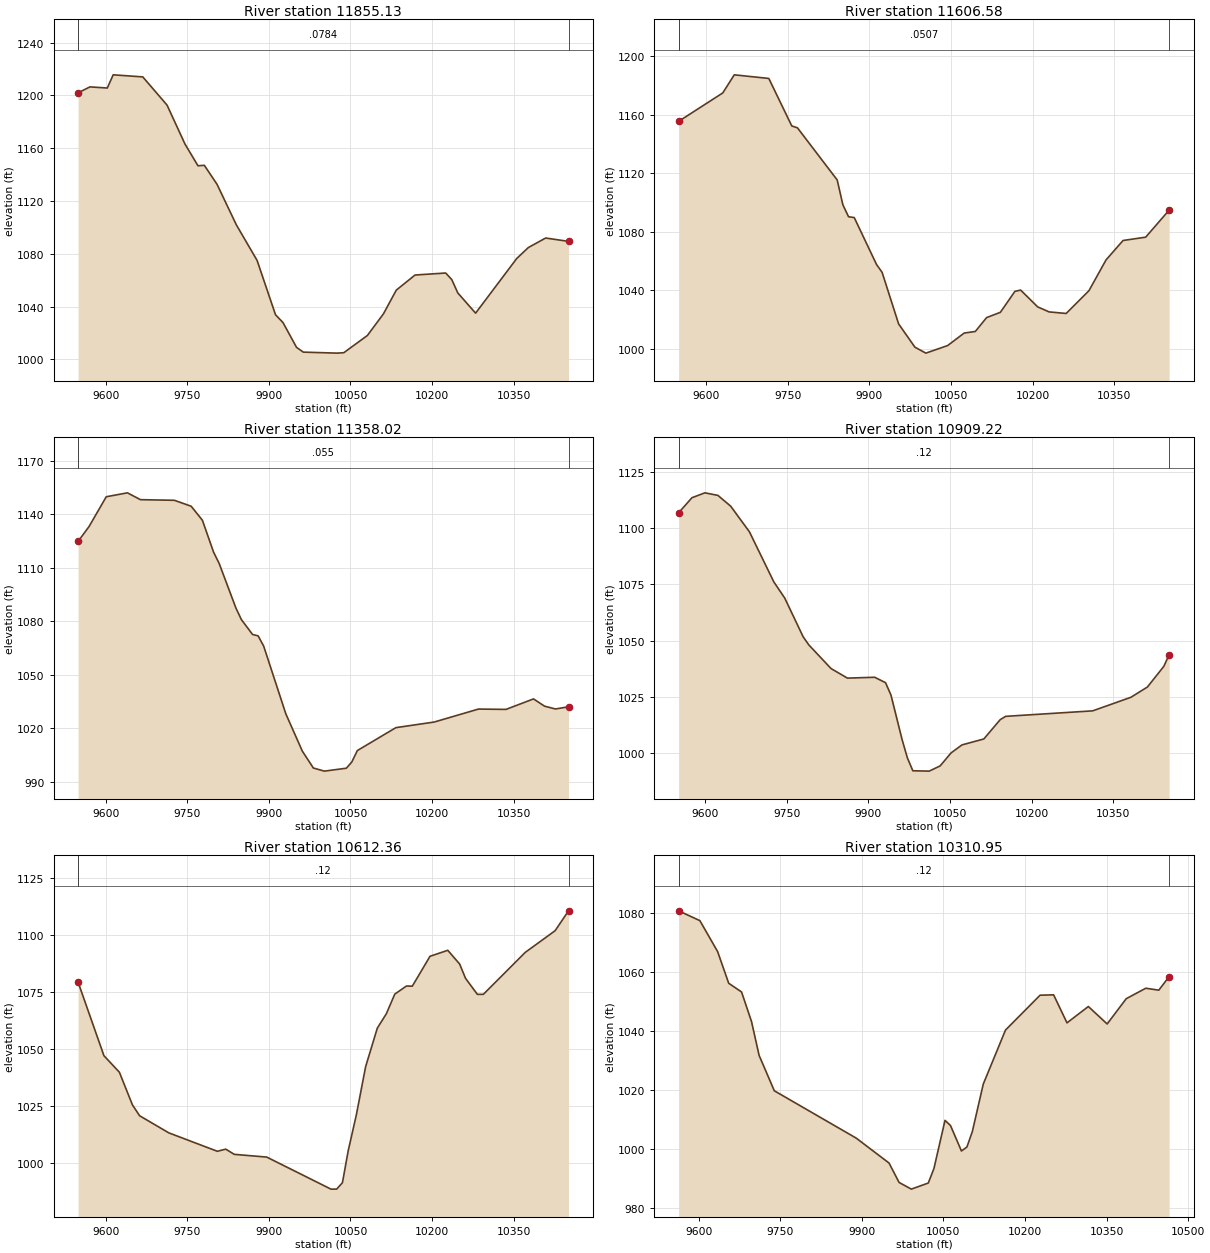
Type RM Length L Ch R = 1 ,11855.13,248.555300,248.555300,248.555300
XS GIS Cut Line= 6
536684.519647039821205.606508253536795.997116477821250.128070131
536888.604743261821298.627380982537229.677037269   821528.813174
537348.140761454821583.795311973537474.807385661821629.647455804
#Sta/Elev= 30
9549.0411201.8869570.8151206.3899602.7771205.5279613.6551215.5299668.0441213.968
9712.6941192.5769745.6521163.094 9769.571146.6239781.1971146.998 9804.661132.549
9840.1291101.8719878.2631074.9219912.1431033.7529925.8551027.8729950.7641009.077
9963.2191005.45910025.331004.69710037.691005.00810081.071018.05510110.611034.448
10134.181052.40510168.691063.85910225.061065.39310236.241060.41610247.321050.302
10280.061034.97810355.731076.41110377.141084.70810408.86 1091.8910450.95 1089.35
#Mann= 3 , 0 , 0
9549.041  0.0784       09549.041  0.0784       010450.95  0.0784       0
#XS Ineff= 2 , 0
       0                               0
Bank Sta=9549.041,10450.95
Exp/Cntr=0.3,0.1

Type RM Length L Ch R = 1 ,11606.58,248.555400,248.555400,248.555400
XS GIS Cut Line= 6
536528.272829571821524.704536054536835.294661748821625.388698978
536915.887835249821641.339760762 536992.76680804821640.549119055
 537048.41905273821649.414307231537396.379535565821753.094429331
#Sta/Elev= 30
9549.0611155.5699630.2411175.0299651.4011187.4089714.8831184.9279757.1321152.418
9767.5691151.1319840.6231115.4739851.0591098.4839861.4951090.2979871.9321089.749
9912.9711057.6189923.1891052.2629953.5481016.9829983.601 1001.0310003.64996.9785
10043.72 1002.1610074.151010.71610094.641011.80310115.351021.29610140.671024.899
10167.421039.244 10177.91040.13410209.31 1028.6110230.261025.18810261.671024.112
10303.561039.70910334.981060.76510366.241074.04910407.871076.31810450.94 1094.81
#Mann= 3 , 0 , 0
9549.061  0.0507       09549.061  0.0507       010450.94  0.0507       0
#XS Ineff= 2 , 0
       0                               0
Bank Sta=9549.061,10450.94
Exp/Cntr=0.3,0.1

Type RM Length L Ch R = 1 ,11358.02,448.804400,448.804400,448.804400
XS GIS Cut Line= 6
 536475.83622726821776.310465814536558.429842596821803.983746677
536645.166706695821828.877100401536808.419423808821866.364285035
536875.578965459 821878.62114678537358.565456637821953.911547446
#Sta/Elev= 30
9549.0251124.8329569.2361133.2019600.8751149.9139639.8161152.1199663.7751148.277
9726.1971147.9269757.0861144.5839777.6771136.7239798.2691118.8059808.5651112.454
9839.4241087.4079849.4941080.9249869.9441072.6319880.1691071.8629890.3941066.093
9931.0751028.1329961.5711007.1159981.772997.706310001.97995.957310042.36997.5951
10052.45 1001.0810062.571007.48710133.461020.34810204.081023.50910285.361030.781
10335.991030.59610386.621036.47910406.881032.40310427.131030.82510450.991032.076
#Mann= 3 , 0 , 0
9549.025   0.055       09549.025   0.055       010450.99   0.055       0
#XS Ineff= 2 , 0
       0                               0
Bank Sta=9549.025,10450.99
Exp/Cntr=0.3,0.1

Type RM Length L Ch R = 1 ,10909.22,296.861500,296.861500,296.861500
XS GIS Cut Line= 6
536494.492085181822208.236687336536646.931055285822298.498442977
 536745.38022309822328.843325106536835.488833126822331.847451088
537147.892848295822309.245147819537364.659530878822326.357619938
#Sta/Elev= 30
9551.072  1106.99575.5211113.5999599.3641115.7839623.2071114.6529646.8051109.835
9681.267 1098.429726.2361076.0749746.1331068.9569779.9471051.7419790.3751048.112
 9831.341037.5589861.4651033.3059911.5171033.686 9931.551031.2679941.5821025.722
9961.648 1006.229971.681997.80649981.713992.057410011.82991.904810031.91994.2266
   100521000.00710072.091003.57810112.271006.22310142.38 1014.8210152.391016.288
10312.511018.73610382.811024.78610413.021029.34210443.221038.53510452.951043.717
#Mann= 3 , 0 , 0
9551.072    0.12       09551.072    0.12       010452.95    0.12       0
#XS Ineff= 2 , 0
       0                               0
Bank Sta=9551.072,10452.95
Exp/Cntr=0.3,0.1

Type RM Length L Ch R = 1 ,10612.36,301.404100,301.404100,301.404100
XS GIS Cut Line= 6
536578.691239705822355.876477939536776.681298243822530.098909216
536833.692073712822571.554020782 536884.72944947822595.164221961
537101.629525371822674.930478151537357.459326569822789.094101287
#Sta/Elev= 30
9549.0641079.3859596.6671047.1199625.0221039.906 9649.111025.5719662.2211020.838
9715.9651013.3379805.2441005.2699820.6321006.2169836.3761003.9329896.0941002.732
10014.06988.702210024.64988.706310035.23991.530510045.821005.48910060.861021.285
10077.841042.29410099.311059.18210115.941065.494 10131.51074.10110152.971077.649
 10163.71077.57610196.261090.66410228.931093.28410250.711087.28410261.591081.011
10283.37 1073.9910294.351073.99910371.311092.36310426.291101.86510450.98 1110.57
#Mann= 3 , 0 , 0
9549.064    0.12       09549.064    0.12       010450.98    0.12       0
#XS Ineff= 2 , 0
       0                               0
Bank Sta=9549.064,10450.98
Exp/Cntr=0.3,0.1

Type RM Length L Ch R = 1 ,10310.95,195.706500,195.706500,195.706500
XS GIS Cut Line= 6
536505.361793595822348.342858156536636.030179402822468.083466107
536702.372064092822565.709968584 536713.30328396822631.424907854
536691.440837633 822856.43374705536831.853398841823130.797755971
#Sta/Elev= 30
9563.2331080.8419602.2971077.5039634.8551067.0189655.2651056.2499678.8851053.296
9697.1911043.2759711.1671031.7599739.1181019.7519889.6071003.6879949.998995.2246
9968.474988.63289990.989 986.36210022.19 988.43710032.58993.380810052.881009.702
10063.021007.955 10083.1999.314710093.111000.63310103.121005.87910123.261022.031
10164.091040.36110227.671052.20110252.561052.31810277.16 1042.81 10316.41048.356
10350.981042.43310386.04 1051.0110421.981054.56410445.941053.90510464.87 1058.51
#Mann= 3 , 0 , 0
9563.233    0.12       09563.233    0.12       010464.87    0.12       0
#XS Ineff= 2 , 0
       0                10053.89       0
Bank Sta=9563.233,10464.87
Exp/Cntr=0.3,0.1

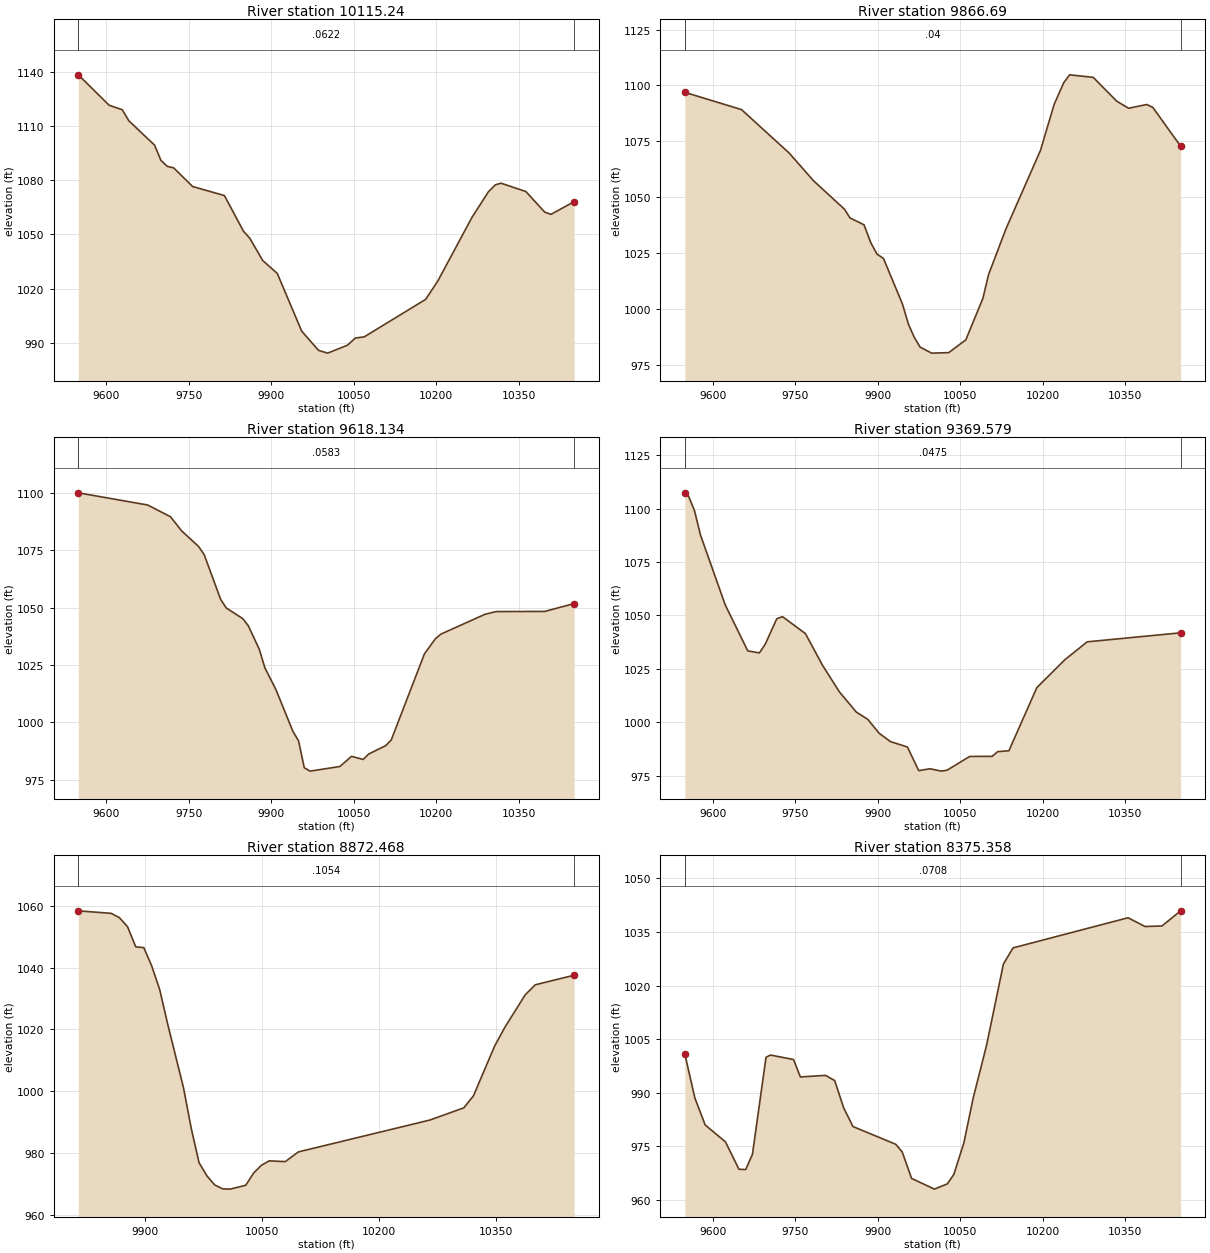
Type RM Length L Ch R = 1 ,10115.24,248.555300,248.555300,248.555300
XS GIS Cut Line= 6
536277.736883541822327.896258811536339.839064188822423.909852915
536518.306458922822721.797592682536592.479998744822809.518274395
 536624.91942438822856.713186675536753.470814738823091.813659547
#Sta/Elev= 30
9549.0311138.5429605.1291121.6639628.9481119.1769640.8571113.0739687.7311099.534
9699.2791091.0999710.8261087.7579722.3741086.9499757.0161076.5769814.7531071.583
9849.3951051.8259860.9421047.902 9884.381035.5729910.924 1028.38 9955.31 996.389
9985.922985.720210002.61  984.1810038.75988.6109 10052.8992.545710069.18993.2086
10180.851014.00710203.151024.30310264.991059.446 10295.21073.77810307.751077.554
10317.831078.43510363.081073.81310397.371062.38810408.811061.15510450.911068.189
#Mann= 3 , 0 , 0
9549.031  0.0622       09549.031  0.0622       010450.91  0.0622       0
#XS Ineff= 2 , 0
       0                               0
Bank Sta=9549.031,10450.91
Exp/Cntr=0.3,0.1

Type RM Length L Ch R = 1 , 9866.69,248.555300,248.555300,248.555300
XS GIS Cut Line= 6
536212.187963917822479.521386927536301.217924126822691.597754599
536388.477936314822843.503535253536466.883376491823104.462272694
536512.673822086823222.945945735536553.070188763823310.998970676
#Sta/Elev= 30
9549.0841096.9089652.3151089.1759739.0671069.6899782.9391057.3889839.6741044.545
9849.5981040.6699875.0641037.6019887.2991029.6169898.6571024.4689910.4541022.527
9944.9171002.1629956.022992.97569966.541987.1619 9977.06982.82729998.098980.1276
10029.19 980.35810060.22 986.07910091.25 1004.6110101.591015.28510132.931035.589
10196.041070.91910220.97 1091.5610238.331101.21410249.061104.74910291.941103.624
10334.821092.92510356.321089.78510389.331091.45510400.331090.17810450.941072.799
#Mann= 3 , 0 , 0
9549.084    0.04       09549.084    0.04       010450.94    0.04       0
#XS Ineff= 2 , 0
       0                               0
Bank Sta=9549.084,10450.94
Exp/Cntr=0.3,0.1

Type RM Length L Ch R = 1 ,9618.134,248.555300,248.555300,248.555300
XS GIS Cut Line= 6
 536121.64896345822435.917752138536191.425711019822706.525100047
536183.644475177822803.417555525536120.301569109823036.678651937
536125.575447495823166.468895839 536160.58332591823312.718768146
#Sta/Elev= 30
9549.185 1100.05 9675.351094.7389716.7171089.6419737.1671083.4449767.841 1076.68
9777.9961073.1319808.1671053.5369818.2231049.8839848.2921045.2179858.2941042.106
9878.2981031.8479888.3571023.8439908.5991014.2659939.282996.17389949.679991.9561
9960.077980.24419970.666978.769510024.83980.783910046.02985.213310067.06983.8497
 10077.3986.235410108.01989.855810118.22992.320810178.55 1029.8610198.551036.472
10208.551038.47410288.771047.12310308.951048.30510397.461048.36510450.861051.797
#Mann= 3 , 0 , 0
9549.185  0.0583       09549.185  0.0583       010450.86  0.0583       0
#XS Ineff= 2 , 0
       0                               0
Bank Sta=9549.185,10450.86
Exp/Cntr=0.3,0.1

Type RM Length L Ch R = 1 ,9369.579,497.110700,497.110700,497.110700
XS GIS Cut Line= 6
535786.542701863822418.988140495535827.334122545822517.798354815
535860.034413587822619.999581636535932.241050906822908.138999865
535979.305041345823144.012684541536026.379524703823286.402966336
#Sta/Elev= 30
9549.0311107.4299555.6181105.9879566.5751099.1739577.5321087.6919622.4271055.031
9663.558  1033.49684.6751032.4439695.2341036.4679716.3331048.4329726.7651049.433
9768.4321041.4999799.3571026.7459830.2831014.1759861.2081004.6829881.8241001.344
9902.441994.85059923.058990.90869953.983988.3676  9974.6977.29989995.217 978.169
10015.85977.066910026.16 977.51810067.31 983.95110108.02983.9822 10118.2986.1912
10138.56986.613710189.451016.20310240.431029.26410280.97 1037.6310450.941041.857
#Mann= 3 , 0 , 0
9549.031  0.0475       09549.031  0.0475       010450.94  0.0475       0
#XS Ineff= 2 , 0
       0                               0
Bank Sta=9549.031,10450.94
Exp/Cntr=0.3,0.1

Type RM Length L Ch R = 1 ,8872.468,497.110600,497.110600,497.110600
XS GIS Cut Line= 6
535325.757149444822991.449470273535401.513698691823018.761908311
535572.142636828 823034.41441038535629.621194544823056.645197505
 535740.05433461823148.983097784535857.202255558823283.517758718
#Sta/Elev= 30
9813.6991058.3589856.0121057.5359866.5011056.1429876.9891053.1949887.477  1046.7
9897.8671046.4379908.0711040.4739918.2751032.8569928.4791021.734 9948.791001.134
9958.823987.89749968.855976.79749978.886 972.5639988.887969.63649998.887968.3683
10008.89  968.2610028.89969.5189 10038.9973.448810048.97975.974910059.04977.4158
10079.62977.166110096.49980.308310265.35990.614910309.12994.586110321.48998.4882
10348.731014.60110361.971020.71810387.921031.14810400.891034.41210450.861037.511
#Mann= 3 , 0 , 0
9813.699  0.1054       09813.699  0.1054       010450.86  0.1054       0
#XS Ineff= 2 , 0
       0                               0
Bank Sta=9813.699,10450.86
Exp/Cntr=0.3,0.1

Type RM Length L Ch R = 1 ,8375.358,248.555300,248.555300,248.555300
XS GIS Cut Line= 6
535004.752824994823234.274680051535282.741573332823438.332285393
535439.100320097823536.522795308 535511.05657501823586.322672403
535611.311298323823664.840801701535731.338590582823766.933696595
#Sta/Elev= 30
9549.0221000.8569567.512988.43819586.155 980.9669622.984976.24449647.537968.5684
9659.814968.4832 9672.09972.74289696.798999.94069704.8571000.5419746.777999.3056
9759.271994.41399804.934994.85659821.614993.41079838.293985.67349854.973980.5266
9932.552975.57649944.431973.44899961.566966.006810003.08963.004310026.62964.4862
10038.39967.105910056.71975.978210073.71988.574310097.881003.22510128.581026.016
10146.151030.55310355.371038.98710386.241036.53510417.111036.69410450.961040.929
#Mann= 3 , 0 , 0
9549.022  0.0708       09549.022  0.0708       010450.96  0.0708       0
#XS Ineff= 2 , 0
       09727.311                       0
Bank Sta=9549.022,10450.96
Exp/Cntr=0.3,0.1

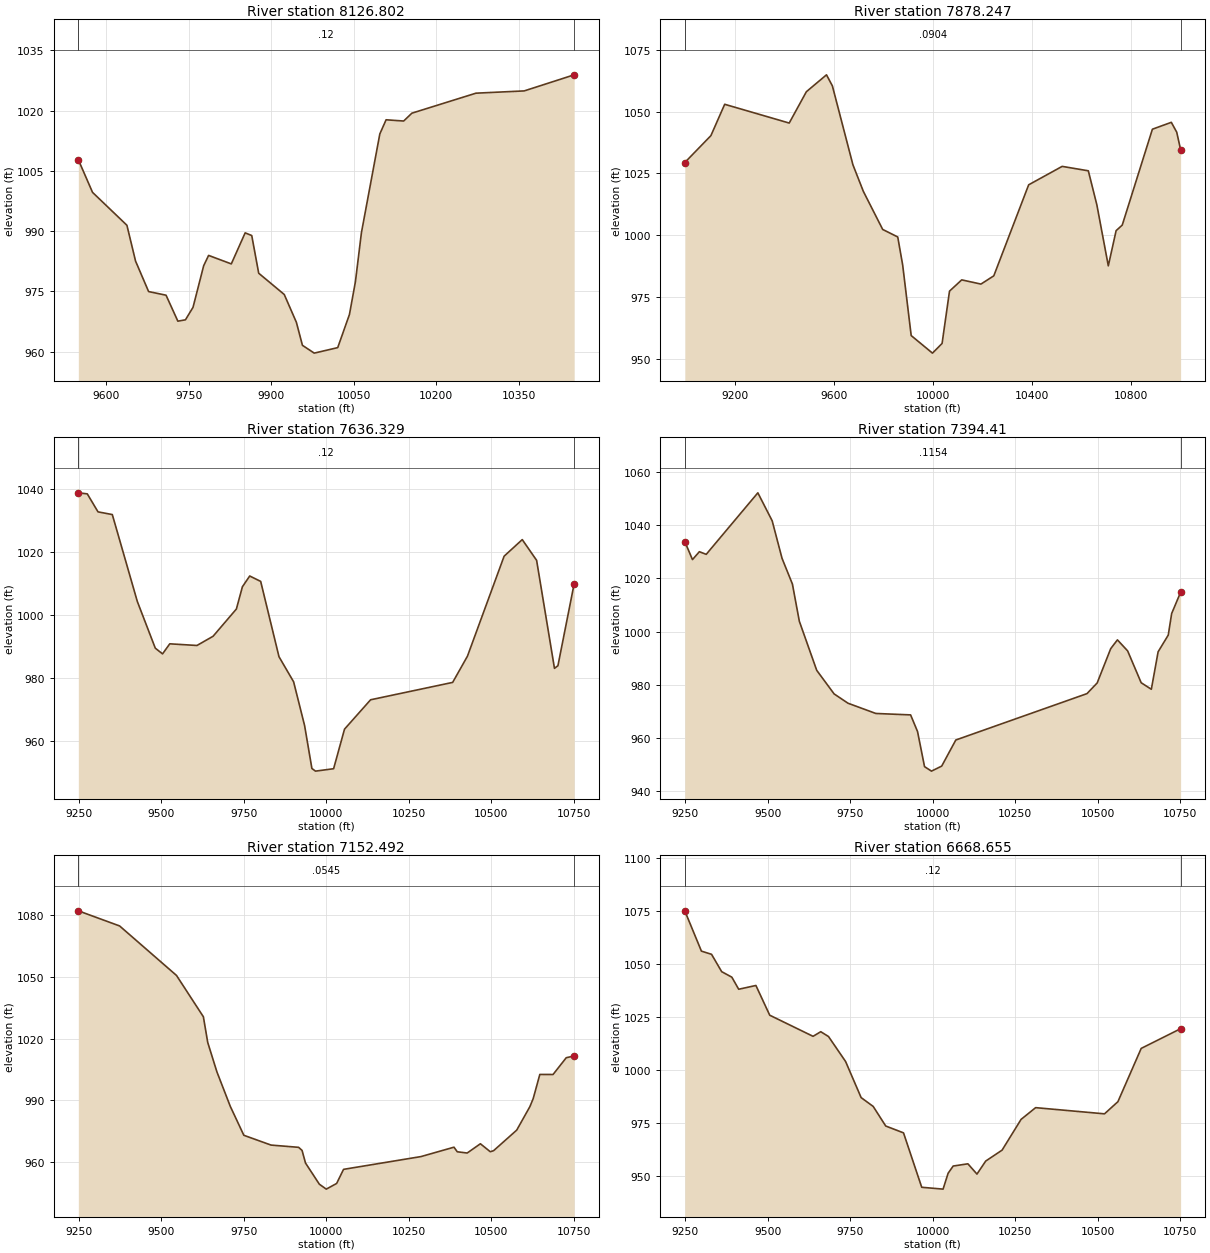
Type RM Length L Ch R = 1 ,8126.802,248.555300,248.555300,248.555300
XS GIS Cut Line= 6
534884.321827081823291.430046747535009.437851553823390.358013704
 535094.77709074823477.571653303535144.269998681823551.789711201
535251.133030968823777.095571438535441.812437311823982.175972691
#Sta/Elev= 30
9549.099 1007.799574.943999.66429637.467991.4747 9653.16982.57149676.935974.9741
9708.645974.07299730.123967.61229743.924967.94729757.726971.0594 9777.08981.4121
9786.054983.97739827.318981.86279852.535989.59049864.514 988.9219877.162 979.542
9923.627974.25369945.686967.33489956.715 961.6029978.177959.658510020.91961.0306
10042.23969.281710053.07977.427510063.99989.626510097.481014.21110108.881017.723
10140.861017.41710155.791019.37110272.341024.346 10360.1 1024.9110450.921028.913
#Mann= 3 , 0 , 0
9549.099    0.12       09549.099    0.12       010450.92    0.12       0
#XS Ineff= 2 , 0
       09838.824                       0
Bank Sta=9549.099,10450.92
Exp/Cntr=0.3,0.1

Type RM Length L Ch R = 1 ,7878.247,241.918400,241.918400,241.918400
XS GIS Cut Line= 6
534150.287154169823276.089841841534491.718278288823449.744770862
534774.728016871823621.060797897534961.096697066823750.712196701
 535467.80419997824149.024186467 535839.41241515824334.073387522
#Sta/Elev= 30
8999.0561029.4229104.492 1040.279160.152 1052.919420.6391045.3439490.0031057.988
 9571.191064.7929594.8881060.346 9677.831028.5189720.0531017.7669798.0681002.434
9858.824999.39839878.731988.10649913.099959.6363    9999952.552410037.86956.4545
10067.81977.543710117.07982.093310194.83980.398710246.67983.729610387.41 1020.43
10522.651027.86710628.291026.08510662.881012.28610708.98987.758210740.511001.944
10765.271004.193   108871042.85810963.391045.63110985.211041.65811000.941034.604
#Mann= 3 , 0 , 0
8999.056  0.0904       08999.056  0.0904       011000.94  0.0904       0
#XS Ineff= 2 , 0
       0                               0
Bank Sta=8999.056,11000.94
Exp/Cntr=0.3,0.1

Type RM Length L Ch R = 1 ,7636.329,241.918500,241.918500,241.918500
XS GIS Cut Line= 6
534189.957973427823683.256387438534386.812659076823765.114284085
534583.756623531 823853.58458121 534929.53024195824016.383479932
535305.216621516824212.162314453535550.742159069824316.825790098
#Sta/Elev= 30
9249.0211038.7239276.1421038.3929308.6321032.6819351.9531031.8189427.7641004.203
9482.155989.39089504.081987.57219526.006990.76949608.362 990.243 9657.17993.1669
9727.791 1001.829745.9961008.8789768.1621012.3099801.4111010.5959856.825986.6835
9901.157978.70529934.406964.81839956.547951.17739967.489950.339310022.31 951.105
10055.33963.668110134.35972.996310382.93978.515910427.73 986.844 10538.81018.596
10593.751023.86810637.251017.28510691.35982.982210701.81983.819410750.961009.833
#Mann= 3 , 0 , 0
9249.021    0.12       09249.021    0.12       010750.96    0.12       0
#XS Ineff= 2 , 0
       0                10162.11       0
Bank Sta=9249.021,10750.96
Exp/Cntr=0.3,0.1

Type RM Length L Ch R = 1 , 7394.41,241.918500,241.918500,241.918500
XS GIS Cut Line= 6
534072.654770938823989.855607574534403.234115606824088.760015542
534983.993370971 824281.03549118535103.351252536824318.342095856
535251.143798433824358.279834413535511.510811111824417.370580156
#Sta/Elev= 30
9249.0081033.8649272.277 1027.089293.1041030.0429313.9311029.0579470.3171052.163
9513.6791041.659 9543.59 1027.559574.9921017.9059595.9391003.9419648.613985.4956
9701.288976.63559743.427973.12929827.705969.28479933.054968.74849954.123962.4646
9975.193949.31379996.263947.627610027.26 949.52110069.98959.320110467.26976.7367
10498.19980.744210539.21993.633410559.53996.930310590.48992.7852 10631.5980.8286
10662.26978.371910682.77992.444710713.53998.726810723.79  1006.810750.971014.836
#Mann= 3 , 0 , 0
9249.008  0.1154       09249.008  0.1154       010750.97  0.1154       0
#XS Ineff= 2 , 0
       0                10191.02       0
Bank Sta=9249.008,10750.97
Exp/Cntr=0.3,0.1

Type RM Length L Ch R = 1 ,7152.492,483.836900,483.836900,483.836900
XS GIS Cut Line= 6
533981.674180735824289.345808065 534466.98799731824376.622647003
 534807.14695915824475.478675998534895.728616021824494.519667977
 535008.95685714824503.955516295535458.906152344824509.723030972
#Sta/Elev= 30
9249.0191082.226 9374.061074.8649546.4471050.7549627.8251030.6419640.9511018.173
9668.6341003.8879709.501986.95729750.421972.93989832.834968.17349916.185967.0787
 9926.67965.60429937.155959.43559979.095949.123410000.07946.727810031.48 949.493
10052.42956.354510286.89962.573410386.91967.143610396.91964.912810426.91964.3048
10466.91968.810910496.91964.936410506.91965.446910576.91975.449210616.92986.9134
10626.92990.815610646.931002.55410686.971002.53510727.01 1010.7110750.941011.565
#Mann= 3 , 0 , 0
9249.019  0.0545       09249.019  0.0545       010750.94  0.0545       0
#XS Ineff= 2 , 0
       0                10266.53       0
Bank Sta=9249.019,10750.94
Exp/Cntr=0.3,0.1

Type RM Length L Ch R = 1 ,6668.655,241.918400,241.918400,241.918400
XS GIS Cut Line= 6
534155.767217725825185.624173245 534615.13019371825030.272123675
534920.527985674824747.384144774535044.881226691824671.740338831
535266.623115696824607.541487371535484.105529489 824586.34063509
#Sta/Elev= 30
9249.0831075.1999299.4211056.1849330.0941054.6889360.7681046.5039391.6391043.887
9412.3151038.2059464.4851039.9849506.3411025.954 9637.551015.9959660.9381018.167
9684.325 1015.919736.1261004.1099783.189987.08619819.747982.91769857.721973.6794
9911.585970.44229966.725944.777710031.37943.905210046.68951.3966   10062954.7934
10106.58955.848610134.03951.002310160.53957.146410210.11 962.29910267.66976.8052
10311.73982.340310520.38979.426410560.94985.154510631.531010.294 10750.9 1019.59
#Mann= 3 , 0 , 0
9249.083    0.12       09249.083    0.12       0 10750.9    0.12       0
#XS Ineff= 2 , 0
       0                10269.12       0
Bank Sta=9249.083,10750.9
Exp/Cntr=0.3,0.1

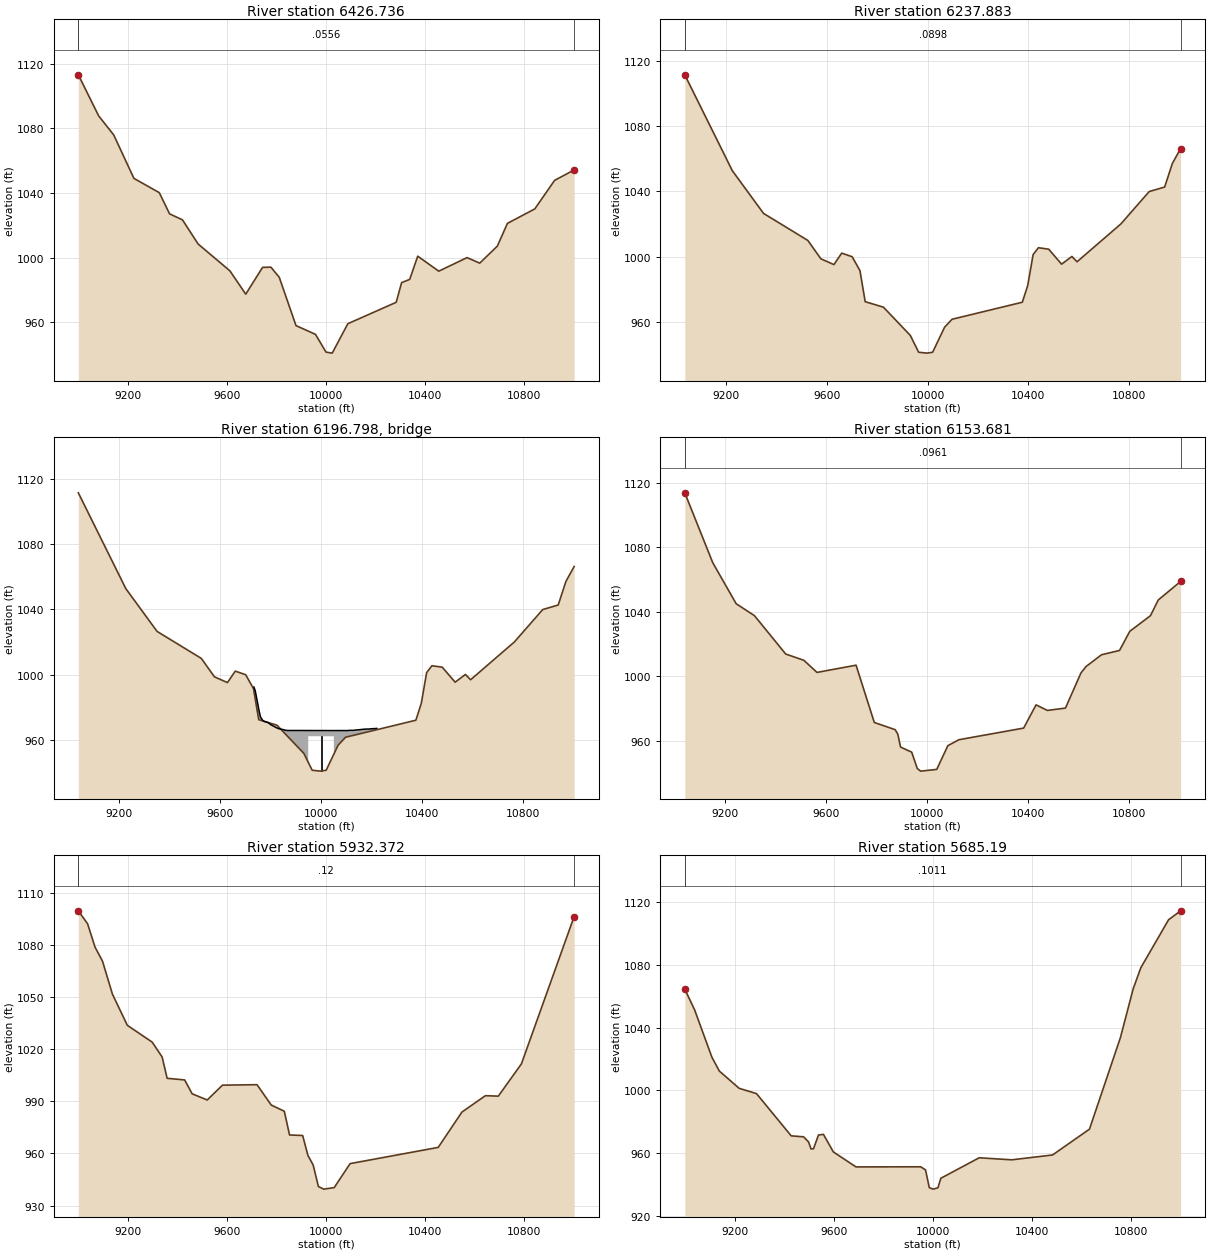
Type RM Length L Ch R = 1 ,6426.736,188.853100,188.853100,188.853100
XS GIS Cut Line= 6
534033.499829006825359.104722667534303.318481717825313.756379248
534572.330016895825232.469974173 535412.63414053824838.957057811
535630.919854857824790.230468734535923.813246648824770.531329565
#Sta/Elev= 30
8999.0811113.1329081.4131087.6949142.025 1075.969223.5251049.0969325.933 1040.27
9367.4641027.1839419.4111023.4649482.7431008.5269611.069991.92479675.059977.5191
9742.972994.06879776.528994.2095  9810.3987.94619877.844958.07569956.645952.6423
    9999941.677210024.12941.048710087.21959.231510282.53972.482410304.28984.6471
10336.91986.6267 10369.41000.99210454.26 991.72610568.471000.10310619.76996.6893
10690.941007.24810731.361021.26110841.98 1030.22 10922.11047.88811000.931054.318
#Mann= 3 , 0 , 0
8999.081  0.0556       08999.081  0.0556       011000.93  0.0556       0
#XS Ineff= 2 , 0
       0                               0
Bank Sta=8999.081,11000.93
Exp/Cntr=0.3,0.1

Type RM Length L Ch R = 1 ,6237.883,84.201800,84.201800,84.201800
XS GIS Cut Line= 5
534112.840465844825478.461294123534928.812688053825264.051571914
  535138.8821325825165.961294138  535435.7571325825052.246016347
535996.955049217824933.322405227
#Sta/Elev= 30
9037.0911111.4489225.4351052.7559349.508 1026.539525.2791009.9589576.976 998.706
9628.674995.15739659.6921002.189 9701.05 999.9769732.068991.43859752.747972.4321
9825.124969.07139931.738951.77159964.847941.45169997.956940.909410020.34941.4524
10067.61956.748210097.28961.660510376.16972.096110397.58982.355310418.991001.301
10439.96  1005.510480.851004.60210531.96 995.41710572.851000.14610593.29996.8959
10767.07 1020.0710879.51 1039.9210940.841042.69510971.511057.16311004.171066.273
#Mann= 3 , 0 , 0
9037.091  0.0898       09037.091  0.0898       011004.17  0.0898       0
#XS Ineff= 2 , 0
       0                               0
Bank Sta=9037.091,11004.17
Exp/Cntr=0.3,0.1

Type RM Length L Ch R = 3 ,6196.798,,,
BEGIN DESCRIPTION:
END DESCRIPTION:
Bridge Culvert--1,0,-1,-1, 0
Deck Dist Width WeirC Skew NumUp NumDn MinLoCord MaxHiCord MaxSubmerge Is_Ogee
30.289900,23.622000,2.6,0, 41, 41, , , 0.95, 0, 0,0,,
 9733.62 9738.85 9749.14 9753.18 9759.43 9769.71 9780.00 9790.28 9795.87 9800.57
 9810.86 9821.14 9831.43 9838.57 9841.72 9852.00 9857.10 9862.62 9868.97 9949.15
 9949.1510050.8510050.8510095.9910103.5710114.5210116.1710125.4810136.4310140.69
10142.3110147.2810158.0010168.1710168.7210179.4510190.1710195.8610200.9010211.62
10220.86
  992.42  990.18  982.01  978.66  974.24  971.76  971.08  970.68  969.93  969.38
  968.53  967.66  966.95  966.71  966.61  966.27  966.03  965.88  965.82  965.80
  965.80  965.77  965.77  965.76  965.76  965.91  965.93  965.87  966.08  966.16
  966.17  966.22  966.38  966.56  966.57  966.69  966.69  966.81  966.90  966.96
  967.09
   -7.58   -9.82  -17.99  -21.34  -25.76  -28.24  -28.92  -29.32  -30.07  -30.62
  -31.47  -32.34  -33.05  -33.29  -33.39  -33.73  -33.97  -34.12  -34.18  -34.20
  962.30  962.27  -34.23  -34.24  -34.24  -34.09  -34.07  -34.13  -33.92  -33.84
  -33.83  -33.78  -33.62  -33.44  -33.43  -33.31  -33.31  -33.19  -33.10  -33.04
  -32.91
 9733.62 9738.85 9749.14 9753.18 9759.43 9769.71 9780.00 9790.28 9795.87 9800.57
 9810.86 9821.14 9831.43 9838.57 9841.72 9852.00 9857.10 9862.62 9868.97 9949.15
 9949.1510050.8510050.8510095.9910103.5710114.5210116.1710125.4810136.4310140.69
10142.3110147.2810158.0010168.1710168.7210179.4510190.1710195.8610200.9010211.62
10220.86
  992.42  990.18  982.01  978.66  974.24  971.76  971.08  970.68  969.93  969.38
  968.53  967.66  966.95  966.71  966.61  966.27  966.03  965.88  965.82  965.80
  965.80  965.77  965.77  965.76  965.76  965.91  965.93  965.87  966.08  966.16
  966.17  966.22  966.38  966.56  966.57  966.69  966.69  966.81  966.90  966.96
  967.09
   -7.58   -9.82  -17.99  -21.34  -25.76  -28.24  -28.92  -29.32  -30.07  -30.62
  -31.47  -32.34  -33.05  -33.29  -33.39  -33.73  -33.97  -34.12  -34.18  -34.20
  962.30  962.27  -34.23  -34.24  -34.24  -34.09  -34.07  -34.13  -33.92  -33.84
  -33.83  -33.78  -33.62  -33.44  -33.43  -33.31  -33.31  -33.19  -33.10  -33.04
  -32.91
Pier Skew, UpSta & Num, DnSta & Num=  ,10000.00, 2 ,10000.00, 2 , 0 , 0 , 0 ,,
    4.00    4.00
  -34.22  965.78
    4.00    4.00
  -34.22  965.78
BR Coef=-1 , 0 , 0 ,, 0 ,,,0.8,0,1,0,
WSPro=,,,, 1 ,,,, 0 ,,,, 0 ,,,,-1 ,-1 ,-1 , 0 , 0 , 0 , 0 , 0
BC Design=,, 0 ,, 0 ,,,,,,

Type RM Length L Ch R = 1 ,6153.681,221.309400,221.309400,221.309400
XS GIS Cut Line= 5
534137.840465844825558.322405234534953.812688053825343.912683025
  535163.8821325825245.822405249  535460.7571325825132.107127458
536021.955049217825013.183516338
#Sta/Elev= 30
9039.4941113.7569150.2911070.4239243.3471044.8969315.7231037.5289439.7961013.694
9512.173 1009.77 9563.871002.2679718.9621006.7639791.338971.18419874.054966.7399
9884.476963.97589895.513955.94419939.659952.76449961.732 942.6299975.138 940.993
10038.99942.056110083.13956.806110126.91960.485810383.92967.711110432.92982.1206
10478.14978.6734 10549.7980.123810611.031001.88810631.471005.93310692.811013.231
10764.36 1015.9210804.861027.76710887.021037.51210917.691047.19811006.581058.762
#Mann= 3 , 0 , 0
9039.494  0.0961       09039.494  0.0961       011006.58  0.0961       0
#XS Ineff= 2 , 0
       0                               0
Bank Sta=9039.494,11006.58
Exp/Cntr=0.3,0.1

Type RM Length L Ch R = 1 ,5932.372,247.182200,247.182200,247.182200
XS GIS Cut Line= 6
534147.545846068825694.580873768534508.463863006825667.361678587
534778.828178425825617.652761085535145.429353569825498.375190992
535706.762567246825281.554722064536073.954892994825196.818222008
#Sta/Elev= 30
8999.0461099.7039036.5571092.2239066.6021078.7719096.6471070.7229136.7071051.762
9196.8521033.7979297.2181024.119 9337.461015.5379357.5871003.2829428.2591002.353
9458.674 994.347 9519.54990.80469580.995999.33269720.566999.60279777.918987.8846
9830.667984.33249851.849970.66129904.804970.34859925.986958.87729947.168953.4031
 9968.35940.97999989.532939.478610032.06940.335310096.38954.169110452.09963.5078
10547.88983.854910642.68993.272810694.76993.010310788.061011.59311000.961096.423
#Mann= 3 , 0 , 0
8999.046    0.12       08999.046    0.12       011000.96    0.12       0
#XS Ineff= 2 , 0
       0                               0
Bank Sta=8999.046,11000.96
Exp/Cntr=0.3,0.1

Type RM Length L Ch R = 1 , 5685.19,247.182200,247.182200,247.182200
XS GIS Cut Line= 6
534255.687284042825860.021838421534724.051595621825877.000814995
534953.707480666825853.610739428535115.032747012825792.958020165
535657.908403145825504.914699355536153.062205213825372.044558374
#Sta/Elev= 30
8999.093 1064.529038.4391051.4729108.4981021.2019138.5241012.3619218.5921001.358
9288.651997.98149428.726971.07059478.734970.46369498.737967.22179508.738962.7479
9518.745 962.8419538.791  971.629558.836972.01299598.927960.83449690.273951.2863
9951.471951.35999971.047949.38949986.249938.0745   10001 937.13210021.16937.9674
10032.82 944.04810187.61957.105210319.19955.8005 10483.9958.889710632.91975.3422
10757.95 1033.7110809.45 1064.7510840.211078.16210952.211108.73211000.931114.443
#Mann= 3 , 0 , 0
8999.093  0.1011       08999.093  0.1011       011000.93  0.1011       0
#XS Ineff= 2 , 0
       0                               0
Bank Sta=8999.093,11000.93
Exp/Cntr=0.3,0.1