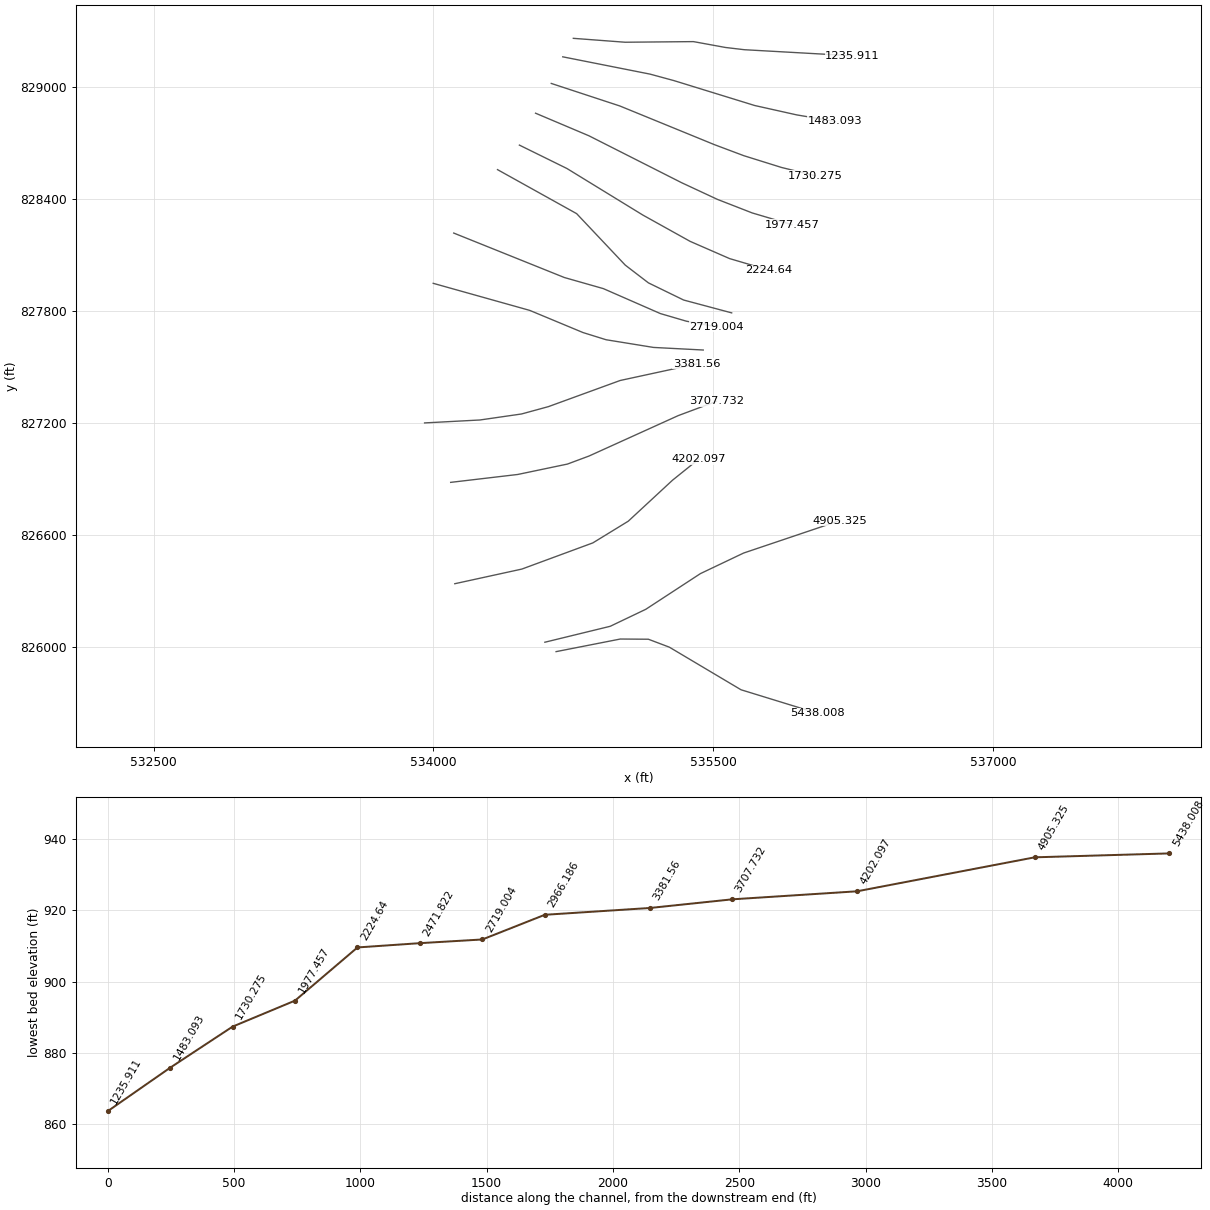
HEC-RAS study 7989_ras.prj: 7989

--- 7989_ras.g01 (geometry) --- (continued)

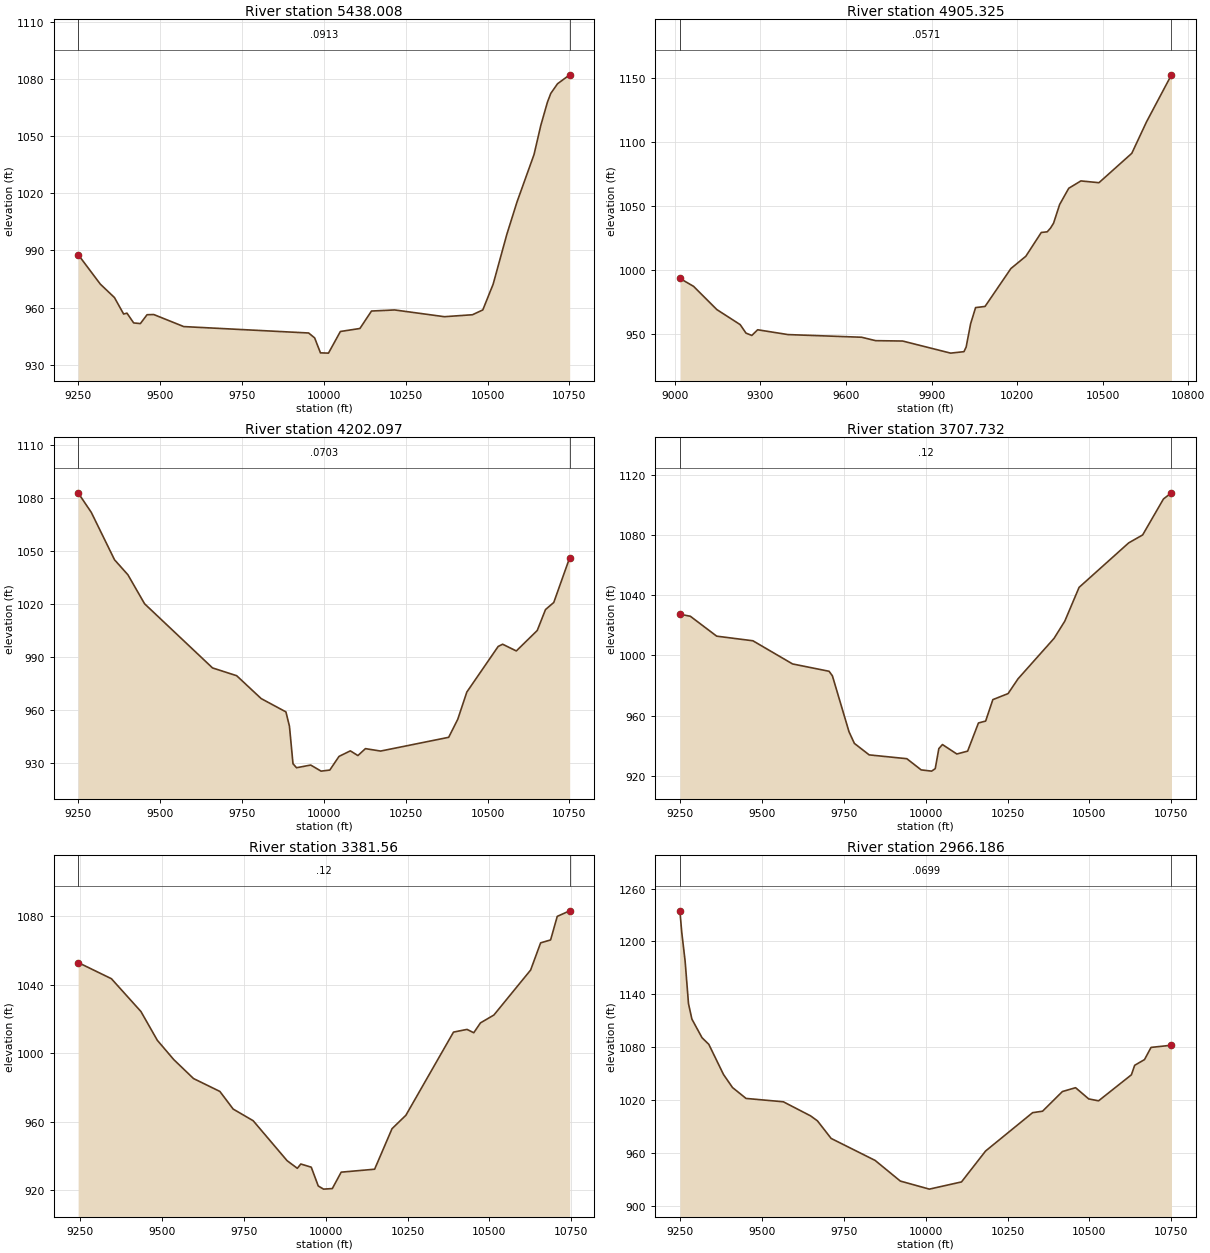
Type RM Length L Ch R = 1 ,5438.008,532.682300,532.682300,532.682300
XS GIS Cut Line= 6
534658.436729853825974.294339506  535002.6427508826041.884230372
535153.193476533826040.825831518535265.647408258825998.228701905
535649.985473372825769.826586039536061.395178381825643.271293939
#Sta/Elev= 30
 9249.12 987.8559316.873972.33079360.125  965.259388.172956.57999398.395  957.05
9418.841951.90599439.286951.55829459.732956.22119480.177956.32149571.842949.9847
9953.394946.61189971.749 944.042 9989.48936.168410013.98936.026510050.39947.4023
   10110948.985210145.42958.157910216.11958.730810368.26955.182210453.78956.2082
10485.44958.731610517.11972.2984   10559998.5476 10590.11015.58610641.941040.425
10662.471055.63410682.951067.99510693.18 1072.5910713.661077.65410750.911082.363
#Mann= 3 , 0 , 0
 9249.12  0.0913       0 9249.12  0.0913       010750.91  0.0913       0
#XS Ineff= 2 , 0
       0    9462                       0
Bank Sta=9249.12,10750.91
Exp/Cntr=0.3,0.1

Type RM Length L Ch R = 1 ,4905.325,703.228500,703.228500,703.228500
XS GIS Cut Line= 6
534598.168319166826024.708000942534948.660005242826110.200978338
535139.276238204826201.263858616535432.355873615826392.713319137
535663.943299056 826502.95048204536179.250673116 826676.71199128
#Sta/Elev= 30
9017.347993.35039065.199987.1625 9146.94968.96999228.682957.23279249.117950.5774
9269.553948.75489289.989 953.1889396.419949.42469654.586947.34419703.627944.6801
 9798.55944.3813 9966.82934.927210013.49936.062810021.18939.656810037.01957.9948
10054.33970.528310087.47971.4296 10178.11001.05710230.471010.64310284.681029.256
10305.571029.79310317.151032.702 10327.81036.53810349.081051.12610381.01 1063.82
10423.581069.56810486.991068.17910602.141091.15610654.061115.88610741.261152.522
#Mann= 3 , 0 , 0
9017.347  0.0571       09017.347  0.0571       010741.26  0.0571       0
#XS Ineff= 2 , 0
       09303.525                       0
Bank Sta=9017.347,10741.26
Exp/Cntr=0.3,0.1

Type RM Length L Ch R = 1 ,4202.097,494.364400,494.364400,494.364400
XS GIS Cut Line= 6
534115.327169484826338.419062457534474.837613284826416.950973074
  534855.6632632826557.401403502535045.423339573826673.714190086
535282.568611393826893.353748456535423.564054339827006.721372028
#Sta/Elev= 30
9249.0711082.8249289.2441071.7879360.3481044.9389401.1041036.484 9452.161020.047
9659.719983.76059733.517979.35659808.395966.41229883.938958.88589894.747950.7723
9905.556929.55839916.365927.29549959.601 928.8159991.402925.377210018.01925.9789
10046.15 933.70710080.77936.846810103.85934.183710126.93938.109810173.16936.7255
 10381.2944.507210408.89 954.68410436.58970.094910532.42995.912810546.02997.1761
10587.84 993.37210651.781004.94810677.011016.77810702.241020.79410750.891046.102
#Mann= 3 , 0 , 0
9249.071  0.0703       09249.071  0.0703       010750.89  0.0703       0
#XS Ineff= 2 , 0
       0                               0
Bank Sta=9249.071,10750.89
Exp/Cntr=0.3,0.1

Type RM Length L Ch R = 1 ,3707.732,326.172600,326.172600,326.172600
XS GIS Cut Line= 6
534093.182331644826881.833527913534452.631589583826924.162683651
534719.180591009826979.933191831534835.376439131827023.240451374
535313.256508932 827239.77547499535518.077455851827316.273325162
#Sta/Elev= 30
9249.0591027.2959281.036 1025.919361.4371012.7179472.1741009.6489593.254994.2754
 9704.85989.40149715.006986.38569765.822949.22589782.178941.52369827.382933.9022
9942.456931.36319986.209923.938410018.21923.118610029.21924.762410040.22938.0791
10051.22940.761110095.22934.492410128.22936.394410161.23955.089910183.23956.3527
10205.23970.586610251.78974.592310282.24984.408610392.251011.25510425.051022.673
10468.711045.09410620.221074.61910662.951079.91310726.531103.79910750.981107.865
#Mann= 3 , 0 , 0
9249.059    0.12       09249.059    0.12       010750.98    0.12       0
#XS Ineff= 2 , 0
       0                               0
Bank Sta=9249.059,10750.98
Exp/Cntr=0.3,0.1

Type RM Length L Ch R = 1 , 3381.56,415.373800,415.373800,415.373800
XS GIS Cut Line= 6
533953.335153482827200.607210524 534250.02803723827216.305270093
534473.208770406827248.552799223534617.423214248827287.968767095
 535001.96120454827428.067313569 535412.36473508827516.959585666
#Sta/Elev= 30
9243.3571053.0239345.0911043.5669435.2031024.4299485.3371007.6119535.471996.3539
9595.878 985.2749676.493977.73159717.128967.43399778.236960.63169881.733937.3258
 9913.14932.83939923.751935.35349955.717933.49759977.028922.52999993.238920.6865
10020.03921.016910047.13930.598310149.27932.311610202.44 955.97910244.75963.8076
 10390.31012.38910431.631013.95910452.161012.01310472.661017.76510513.671022.359
10625.941048.63410656.471064.50910686.961066.20910707.281079.97510745.261083.209
#Mann= 3 , 0 , 0
9243.357    0.12       09243.357    0.12       010745.26    0.12       0
#XS Ineff= 2 , 0
       0                               0
Bank Sta=9243.357,10745.26
Exp/Cntr=0.3,0.1

Type RM Length L Ch R = 1 ,2966.186,247.182200,247.182200,247.182200
XS GIS Cut Line= 6
 533999.60602512827949.037865586534517.145527421827803.915505096
534802.854703742827685.035377785534926.680367913827646.512105734
 535180.82093093827605.296114312535447.380702034827591.466143365
#Sta/Elev= 30
9249.0411234.6919254.6211210.5579264.9641177.6859275.3071129.3669285.6511111.818
9316.6811090.6459337.3681083.1539382.2481048.9239409.7711034.0999451.1451021.728
 9565.151017.9169648.4011001.9169669.223996.30779711.096976.3292 9845.38951.3979
 9922.49927.924510011.15918.7764 10109.4926.954310182.99962.039410326.681005.571
10357.061007.23510417.671029.54610457.931033.91510498.14 1021.1710528.211019.026
10628.451048.54410638.471059.33110668.491065.809 10688.51079.643 10750.9 1082.14
#Mann= 3 , 0 , 0
9249.041  0.0699       09249.041  0.0699       0 10750.9  0.0699       0
#XS Ineff= 2 , 0
       0                               0
Bank Sta=9249.041,10750.9
Exp/Cntr=0.3,0.1

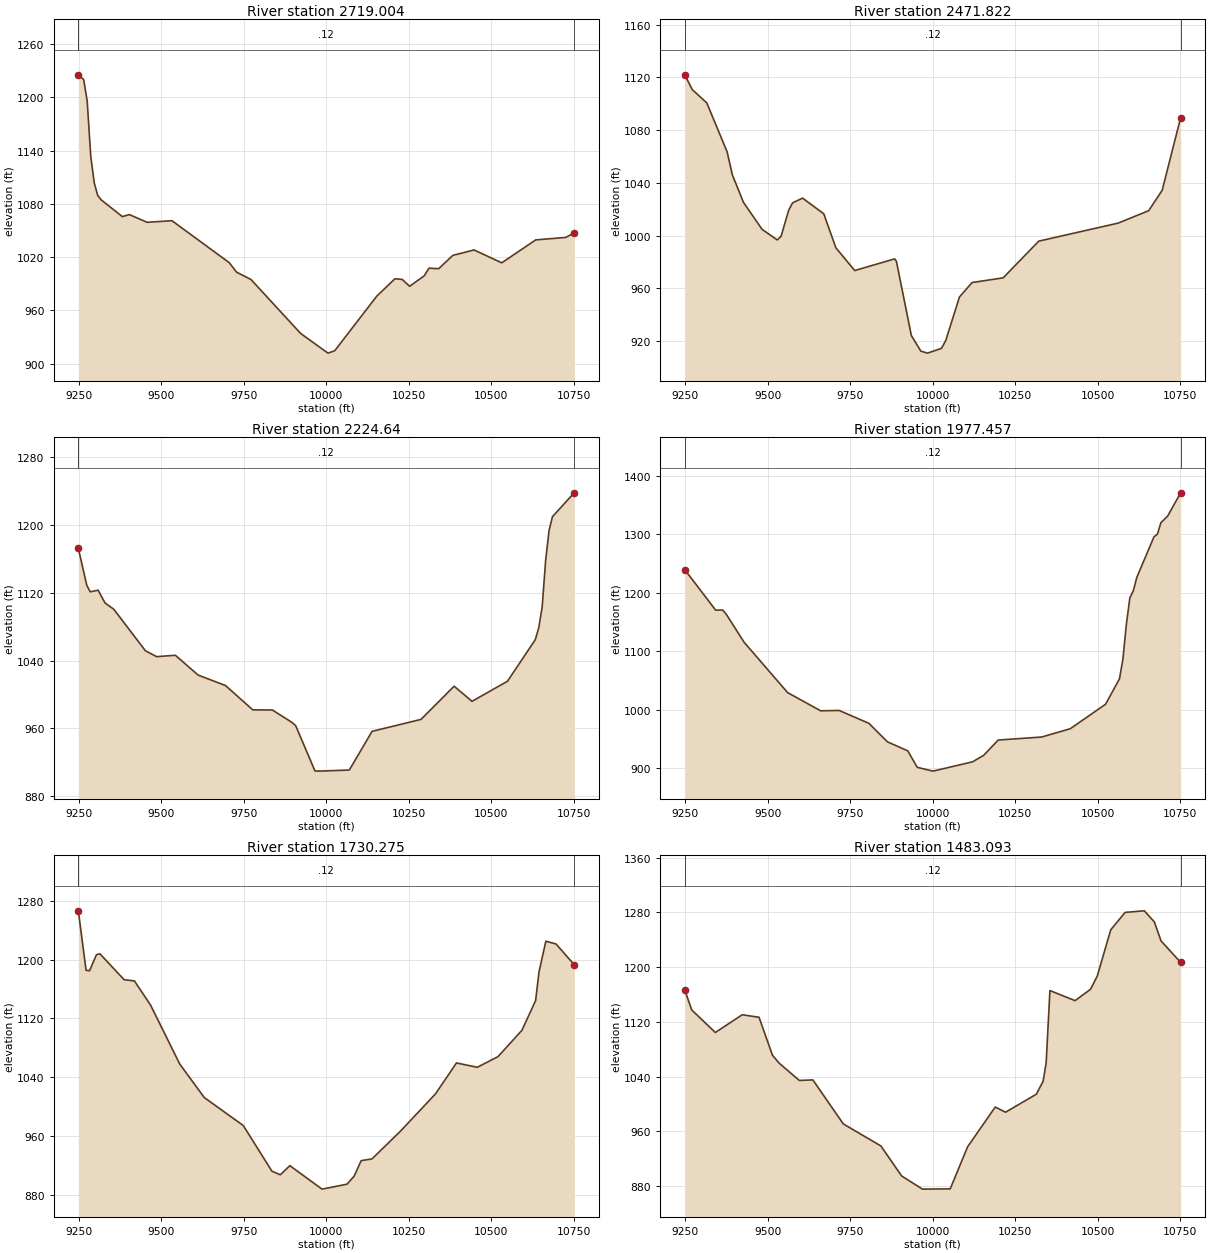
Type RM Length L Ch R = 1 ,2719.004,247.182200,247.182200,247.182200
XS GIS Cut Line= 6
534109.630036049828218.520174143534702.922500009827980.075688637
534911.835129796827920.632997971535217.634792559827786.799421893
535357.067272766827745.984920701535519.830964755827716.017917255
#Sta/Elev= 30
9249.0451225.4629265.3521220.0829275.9611195.608 9286.571134.027 9297.181103.811
9307.7891089.4889318.3981084.521 9382.33  1065.79403.756 1067.969457.3211059.253
9532.6081061.0879706.4681013.6819728.2791003.0999771.901994.84969922.342934.0434
10005.11911.841410025.66914.5277 10153.1976.083210208.28995.696210230.36994.8375
10252.44987.137510296.61998.921610311.271007.574 10340.51006.97910383.471021.996
10447.741028.10710531.571013.58610634.421039.44410725.73 1042.26 10750.91047.446
#Mann= 3 , 0 , 0
9249.045    0.12       09249.045    0.12       0 10750.9    0.12       0
#XS Ineff= 2 , 0
       0                               0
Bank Sta=9249.045,10750.9
Exp/Cntr=0.3,0.1

Type RM Length L Ch R = 1 ,2471.822,247.182100,247.182100,247.182100
XS GIS Cut Line= 6
534344.338226773828558.612505099534768.662591062 828322.55037115
 535029.07110656828046.775785198535153.454779142827951.451738263
535342.277615813827859.455160554535599.843103757 827790.59101309
#Sta/Elev= 30
  9249.11121.9189271.7971110.6959315.7371100.6159377.3421063.4739393.1291046.051
9426.7781025.1899483.3231004.6579529.164 996.6739540.784999.52849564.0241019.383
9575.6441024.7999605.821  1028.4 9670.051016.4889706.574990.76389763.751 973.457
9884.695982.3004 9890.01980.47629935.353924.12789964.094 912.306 9984.11910.8044
10026.62914.432910039.17920.161810081.07953.3931 10119.3964.361710213.44967.9093
10321.13 995.74810561.54 1009.42   10654 1018.83   10695 1034.3110750.861089.355
#Mann= 3 , 0 , 0
  9249.1    0.12       0  9249.1    0.12       010750.86    0.12       0
#XS Ineff= 2 , 0
       0                               0
Bank Sta=9249.1,10750.86
Exp/Cntr=0.3,0.1

Type RM Length L Ch R = 1 , 2224.64,247.182200,247.182200,247.182200
XS GIS Cut Line= 6
534461.674546455828690.141232801 534716.97739202828564.379342146
535123.522370826828315.068084805535377.089508306828173.980192296
 535589.04147367828081.498363286535798.733984231828019.854033771
#Sta/Elev= 30
9249.0481172.6469274.7431128.9079285.1451121.2729308.9851123.2549329.823 1108.21
9356.6651100.6389452.4521051.6249486.3311044.7919543.0221046.3899611.9211022.997
9694.6751010.6939777.601 981.9429836.834981.78399895.856967.22459907.505963.2664
 9965.75909.88549977.399909.5986 10069.9910.9124 10138.9956.5815 10287.2970.6996
 10387.31009.883 10441.6992.017810549.071015.74610633.241064.82810643.761078.866
 10654.11103.47310664.43 1157.7410674.761193.28410685.091209.98510750.951238.203
#Mann= 3 , 0 , 0
9249.048    0.12       09249.048    0.12       010750.95    0.12       0
#XS Ineff= 2 , 0
       0                               0
Bank Sta=9249.048,10750.95
Exp/Cntr=0.3,0.1

Type RM Length L Ch R = 1 ,1977.457,247.182200,247.182200,247.182200
XS GIS Cut Line= 6
534548.297198118828861.159742773534834.550542594828740.033554079
535331.226972441828488.610741537535523.688357084828398.966467288
 535710.22279249828326.315535678535922.851380675828263.440555101
#Sta/Elev= 30
9249.025 1239.439342.4551170.2339364.0071170.3159374.783 1163.129428.8611115.147
9560.4141029.1269660.642997.89679716.522 998.5299806.639976.53619862.962944.7597
9924.538929.35879953.078901.1592   10001894.653310120.81910.627310154.11 921.583
10198.51947.862410330.38953.049710416.81967.268310523.61 1009.1510565.711052.586
10576.211086.61210586.711146.62310597.221191.36710607.721203.43110618.221226.233
10670.321295.77810680.681300.33510691.041319.68810711.761331.30110750.97 1371.05
#Mann= 3 , 0 , 0
9249.025    0.12       09249.025    0.12       010750.97    0.12       0
#XS Ineff= 2 , 0
       0                               0
Bank Sta=9249.025,10750.97
Exp/Cntr=0.3,0.1

Type RM Length L Ch R = 1 ,1730.275,247.182100,247.182100,247.182100
XS GIS Cut Line= 6
534632.587164414829020.731321555535000.256770985828899.865604949
535507.230776049828692.538862776535665.116283381828633.301096584
535867.493997755828570.122723186536048.537342711828525.761915805
#Sta/Elev= 30
9249.0281266.5989272.4981185.634 9282.971184.8729303.9131206.8179314.3851208.031
9387.6871172.7869419.1021171.0129467.7731138.2279556.3291057.7689630.5481012.152
9748.661974.02799835.521911.76729860.835906.89479889.824 919.3219987.271887.3418
10062.77894.056310084.35904.900510105.93926.182110138.31928.470110224.22966.0583
10331.03  1017.2 10394.51059.28210457.661053.41810520.281067.87310592.951103.908
10634.241144.36610644.561183.46410665.211225.24310696.08 1221.3910750.971193.288
#Mann= 3 , 0 , 0
9249.028    0.12       09249.028    0.12       010750.97    0.12       0
#XS Ineff= 2 , 0
       0                               0
Bank Sta=9249.028,10750.97
Exp/Cntr=0.3,0.1

Type RM Length L Ch R = 1 ,1483.093,247.182200,247.182200,247.182200
XS GIS Cut Line= 6
534694.136337263829163.444429735535162.352395426829070.667500834
 535290.42430785829035.871371645535723.461444441828902.359141198
535948.562356467828852.085146592536153.591181299828817.298870913
#Sta/Elev= 30
9249.0351166.4369270.2781137.3479341.5481104.571    9423 1130.469473.9071126.806
9514.633 1071.379534.9961059.6649596.0851034.5219636.9971035.3259729.127971.0701
9843.114938.80939905.938895.00669968.987875.785610053.09876.202410105.66937.5787
10189.38995.644710220.67988.130610313.92  1014.410334.491033.43110343.671060.364
10355.071165.79410431.381151.05210478.061167.698 10498.51187.01610539.37 1254.63
10582.941279.968   106411282.25510671.421266.09510691.671238.30610750.981206.989
#Mann= 3 , 0 , 0
9249.035    0.12       09249.035    0.12       010750.98    0.12       0
#XS Ineff= 2 , 0
       0                               0
Bank Sta=9249.035,10750.98
Exp/Cntr=0.3,0.1

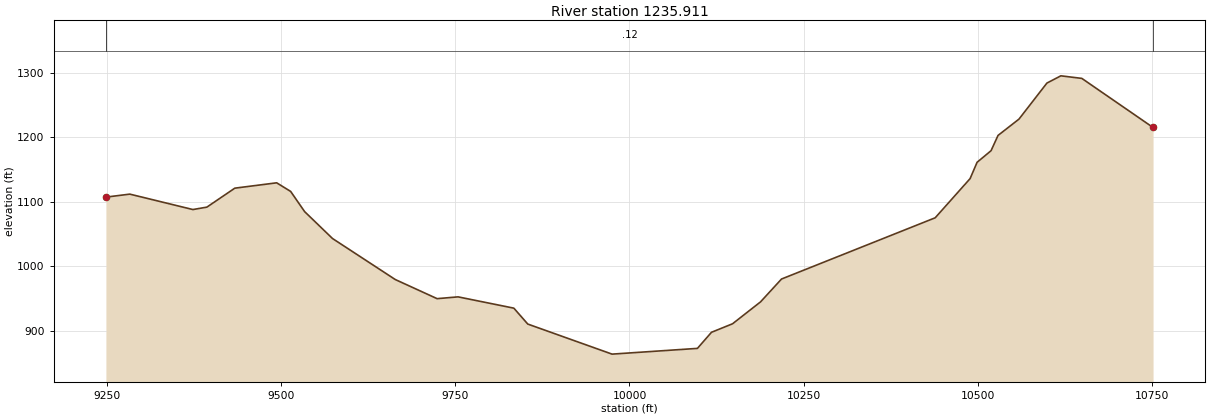
Type RM Length L Ch R = 1 ,1235.911,247.182100,247.182100,247.182100
XS GIS Cut Line= 6
534750.861594039829262.565226813535028.336113116829241.662144353
535394.737778708 829244.99133176 535567.07871829829213.490955455
535667.948985145829201.563036876536247.032500693829169.084125678
#Sta/Elev= 30
9249.1011107.1969283.4111111.8339373.8641087.9079393.9491091.6629433.9981121.088
9494.0721129.3869514.0971116.0259534.114 1084.719574.1141042.9669664.123  979.32
9724.145949.63729754.155952.42719834.183934.90619854.188910.2098 9975.06863.5703
 10097.5872.479110117.64897.444510147.85910.657210188.05944.689410218.11 980.113
10438.511075.12510488.58 1135.9510498.591161.23510518.621179.23510528.631202.919
10558.671228.24610598.731284.15810618.751295.40310648.791291.42210750.961215.272
#Mann= 3 , 0 , 0
9249.101    0.12       09249.101    0.12       010750.96    0.12       0
#XS Ineff= 2 , 0
       0                               0
Bank Sta=9249.101,10750.96
Exp/Cntr=0.3,0.1