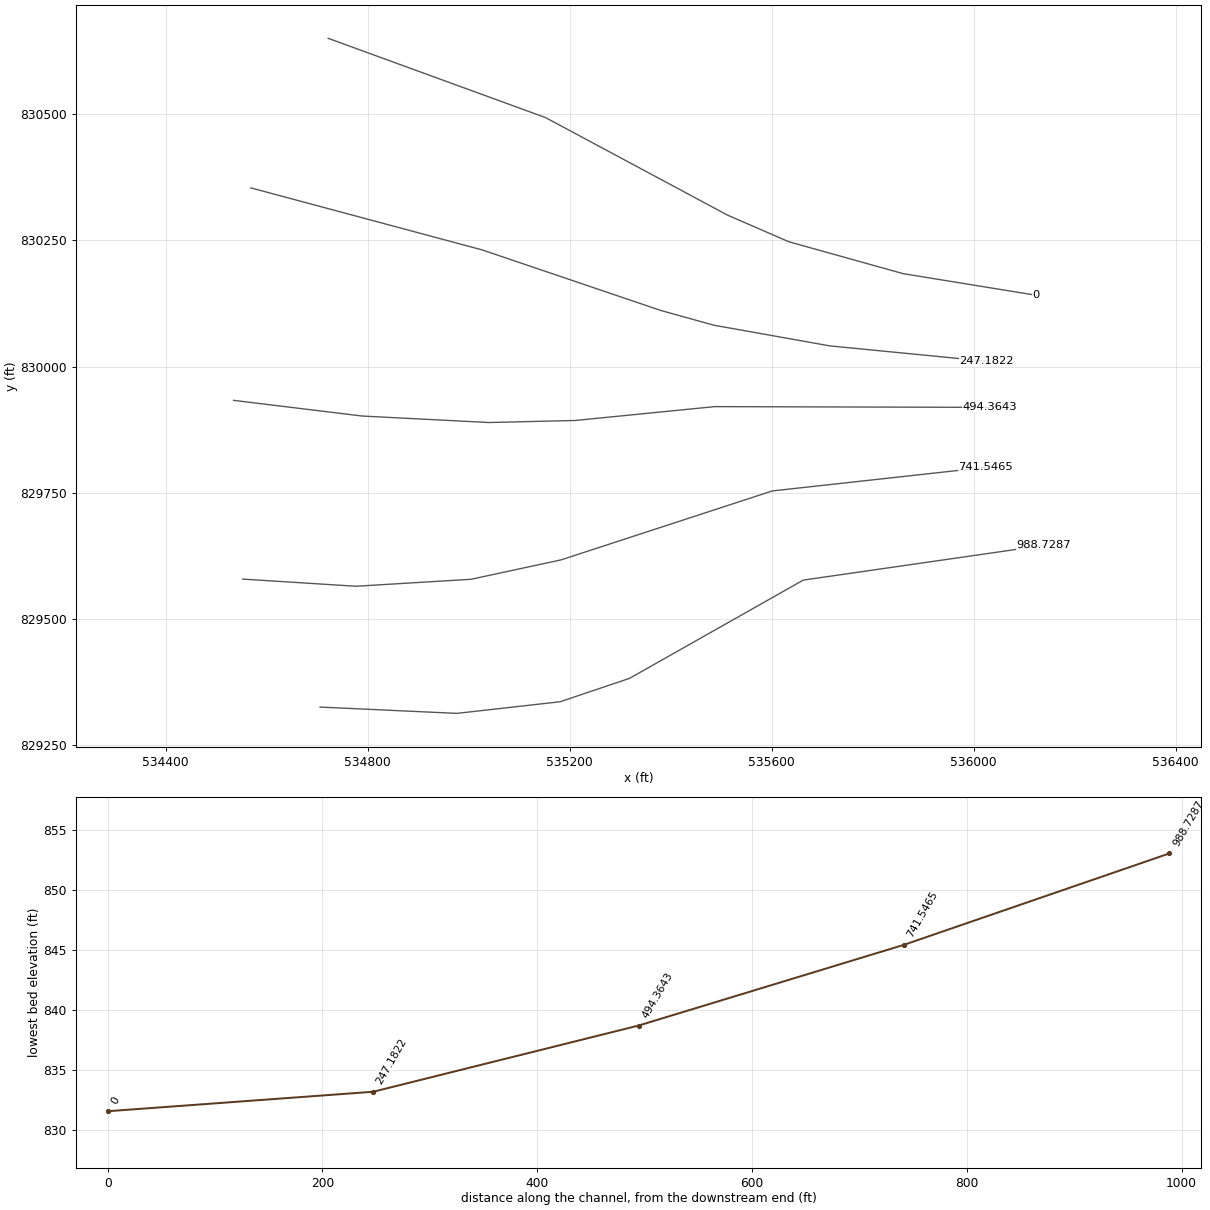
HEC-RAS study 7989_ras.prj: 7989

--- 7989_ras.g01 (geometry) --- (continued)

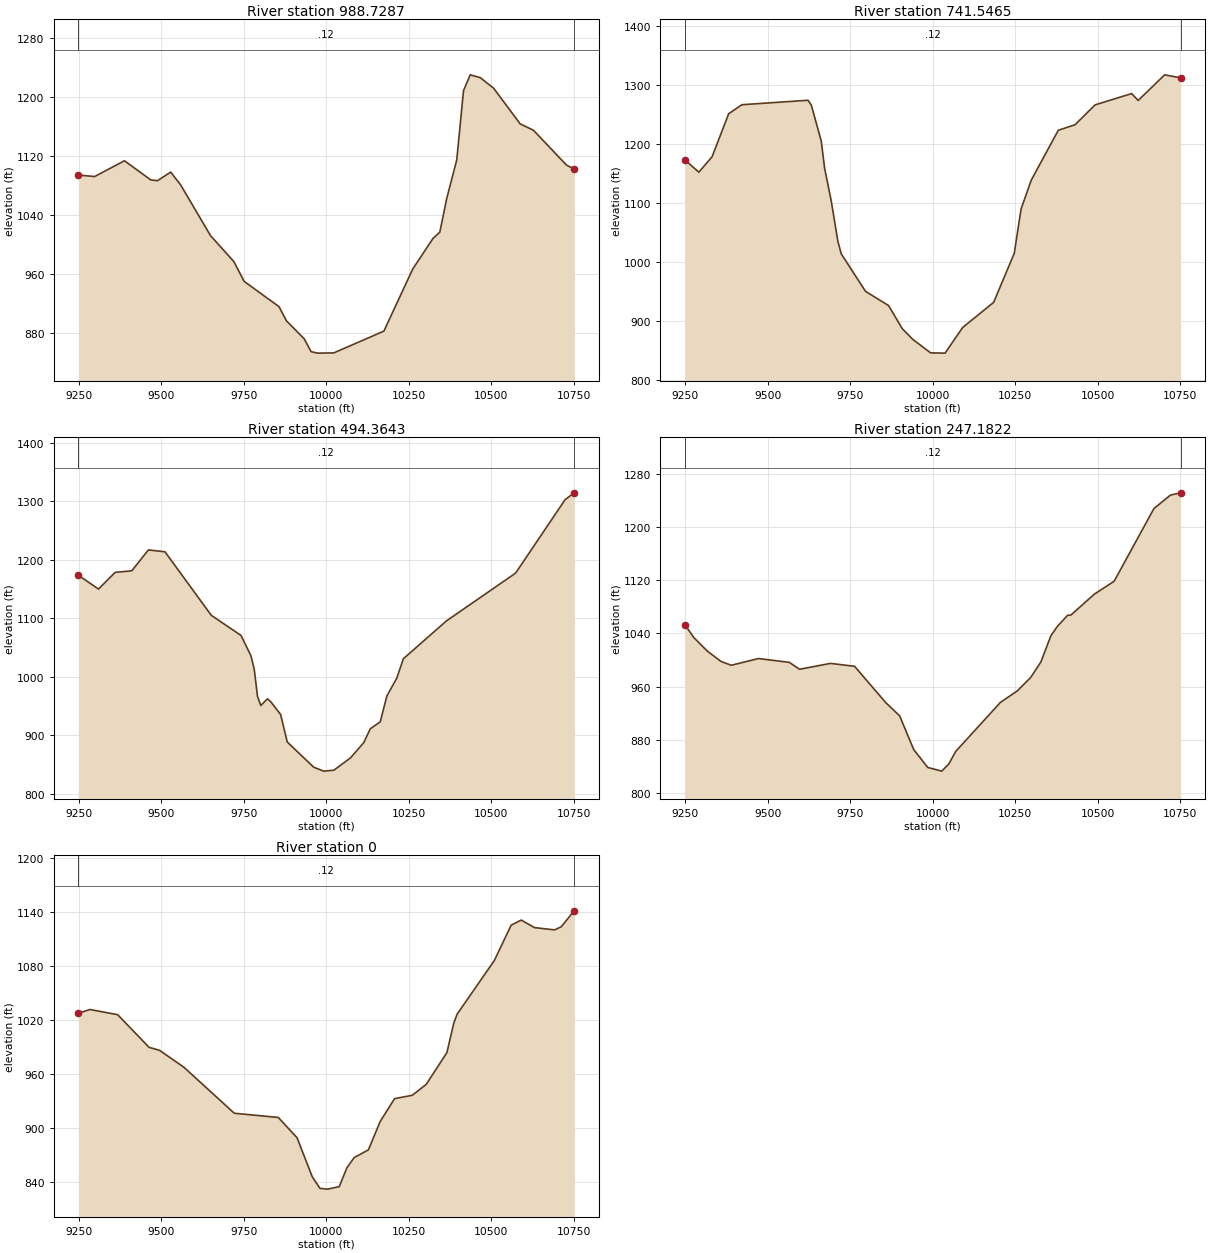
Type RM Length L Ch R = 1 ,988.7287,247.182200,247.182200,247.182200
XS GIS Cut Line= 6
 534705.74023722829325.752558092534976.642599513829313.280067578
535181.034781285829336.284252382535318.537394899829382.644860738
535662.493914993829577.173430732536138.182025069829645.697136513
#Sta/Elev= 30
9249.1471094.0649298.5711092.0189388.8371113.3939468.8691087.3729488.8691086.417
9528.8771098.0429558.9041080.8379649.3651012.1399720.326976.86269751.252950.2154
9857.074915.87369879.292896.85879933.741872.15039954.139854.97339973.728853.0129
10022.84853.318210174.52882.758810262.31967.102710323.291008.14410344.061016.761
10364.711061.87910395.34 1114.5910415.771208.30210436.151229.69610466.551225.859
10506.891211.65610587.421163.28910627.561154.73410727.691107.536 10750.9 1102.23
#Mann= 3 , 0 , 0
9249.147    0.12       09249.147    0.12       0 10750.9    0.12       0
#XS Ineff= 2 , 0
       0                               0
Bank Sta=9249.147,10750.9
Exp/Cntr=0.3,0.1

Type RM Length L Ch R = 1 ,741.5465,247.182200,247.182200,247.182200
XS GIS Cut Line= 6
534552.578831424829579.154346902 534776.89252449829564.975990779
535004.977827985829578.831917171535182.879708679829617.177510541
 535601.19651029 829753.71393241536023.334432331829800.241448953
#Sta/Elev= 30
9249.1381173.0459291.7221152.1049331.876 1178.319382.0111251.0969422.039 1266.37
9622.2471273.9449632.3011265.8949662.4641204.6569672.5191159.1469692.6281103.459
9712.8411034.923    97231013.6919796.605950.03769866.315 926.0619908.074 886.695
9939.682868.7308 9993.72 845.84810037.52845.415710090.55888.744810184.59931.4821
10246.991014.47210267.621089.50110298.551138.63110380.36 1223.0910431.231232.499
10491.821266.117 10602.41285.26810622.431273.63310702.521317.05110750.911311.855
#Mann= 3 , 0 , 0
9249.138    0.12       09249.138    0.12       010750.91    0.12       0
#XS Ineff= 2 , 0
       0                               0
Bank Sta=9249.138,10750.91
Exp/Cntr=0.3,0.1

Type RM Length L Ch R = 1 ,494.3643,247.182100,247.182100,247.182100
XS GIS Cut Line= 6
 534534.48725359829933.064527754 534788.86573519829902.050521799
535040.170818832829889.177188226535211.257413179829893.237656045
535487.194063941829920.661363157 536032.27367453829919.138384354
#Sta/Elev= 30
9249.0541173.8659310.1121150.0629360.5621178.6619410.9921181.3079461.2531217.026
9511.4971213.8859651.798 1105.219741.8481070.7499771.857 1036.169781.8571013.032
9791.857966.53649801.858950.93319821.858962.36799831.858957.48819861.866935.5559
9881.888888.5748  9962.1 845.3759992.432838.703510022.98840.251510073.38861.2931
10113.51887.409710133.55911.208310163.59923.015710183.61 967.20210213.63997.6991
10233.631030.90610363.661095.45510573.671177.42410723.691303.09410750.971314.696
#Mann= 3 , 0 , 0
9249.054    0.12       09249.054    0.12       010750.97    0.12       0
#XS Ineff= 2 , 0
       0                               0
Bank Sta=9249.054,10750.97
Exp/Cntr=0.3,0.1

Type RM Length L Ch R = 1 ,247.1822,247.182200,247.182200,247.182200
XS GIS Cut Line= 6
534568.833334744 830353.71852314535026.583940444830230.977050341
535380.344413788830111.033558529535485.616217566830081.818355188
535715.456673923830040.848898876536025.540896454830010.538543519
#Sta/Elev= 30
 9249.021053.3559276.0511033.9769317.372 1013.459358.694997.97859389.684992.2027
9472.3271002.2919565.573996.54969596.722986.21889690.169994.99269763.249990.6651
9857.632936.1778 9899.98916.12119942.446865.56839984.912838.712310027.32 833.202
10048.51 843.779 10069.7862.827910205.19936.472310256.22 953.68110297.03974.0107
10327.64997.1382   103581036.57910378.231050.93610408.571067.18810418.681067.633
10489.221098.846 10549.61118.39410670.121227.569 10720.31247.78210750.951251.167
#Mann= 3 , 0 , 0
 9249.02    0.12       0 9249.02    0.12       010750.95    0.12       0
#XS Ineff= 2 , 0
       0                               0
Bank Sta=9249.02,10750.95
Exp/Cntr=0.3,0.1

Type RM Length L Ch R = 1 ,       0,0.000000,0.000000,0.000000
XS GIS Cut Line= 6
534721.870688106830649.858080767535152.198959417830492.932534769
535512.704778842830299.731015545535633.917498777830247.069296411
535860.209378786830183.927056433536123.687916545830141.127665964
#Sta/Elev= 30
9249.0291027.2829283.8911031.4419368.0741025.7179463.272 989.3689495.073986.0297
9568.811967.21629721.375916.02159854.609911.33449911.536888.79019957.624845.3554
9981.008832.4324 10004.4831.583710039.39 834.394 10062.4855.237110084.49866.6234
 10127.8875.330810163.29906.785310206.94932.262310260.55935.991610302.85948.1408
10365.46983.500410386.031015.86510396.311026.21210509.171085.98110560.051125.243
10590.541130.99910630.971122.57210691.611120.05310711.831123.52110750.931141.256
#Mann= 3 , 0 , 0
9249.029    0.12       09249.029    0.12       010750.93    0.12       0
#XS Ineff= 2 , 0
       0                               0
Bank Sta=9249.029,10750.93
Exp/Cntr=0.3,0.1